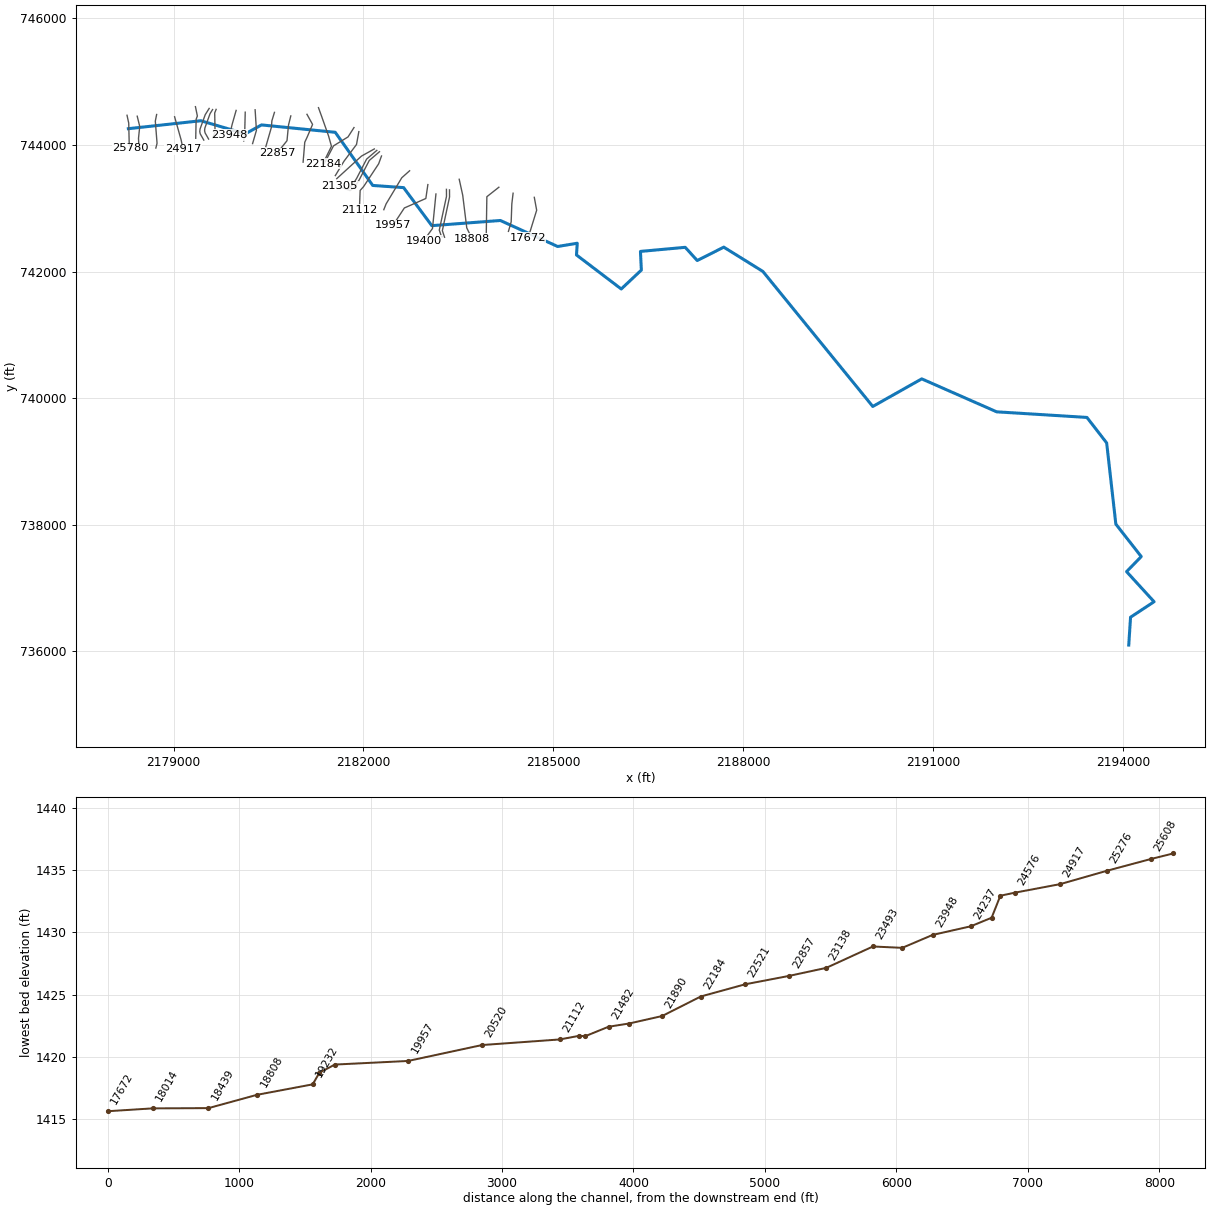
--- TURKEYRN.prj (project) ---

Proj Title=TURKEYRN
Current Plan=p01
Default Exp/Contr=0,0
English Units
Geom File=g01
Flow File=f01
Plan File=p01
BEGIN DESCRIPTION:
---------- MODELED AS PART OF WVEMD CTP PROGRAM, 2023----------
Stream Name: Turkey Run
Flood Zone:  AFH
Upshur County, WV
HEC-RAS Version: RAS 6.3
Vertical Datum: NAVD88
Projection: NAD 1983 StatePlane West Virginia S FIPS 4702 (US Feet)
Terrain: 1-meter LIDAR (FEMA Region III 3DEP collected 2016-2018)
Land Use: 2019 NLCD
Hydrologic Method:
WV SIR2010-5033 regression equations
Additional Model Notes:
Main stem is BUCKHANR_L
END DESCRIPTION:
DSS File=dss
DSS Export Rating Curves= 0
DSS Export Rating Curve Sorted= 0
DSS Export Volume Flow Curves= 0
DXF OffsetX= 0
DXF OffsetY= 0
DXF ScaleX= 0
DXF ScaleY= 0

--- TURKEYRN.p01 (plan) ---

Plan Title=Floodplain
Program Version=6.30
Short Identifier=Floodplain
Geom File=g01
Flow File=f01
Subcritical Flow
K Sum by GR= 0
Std Step Tol= 0.01
Critical Tol= 0.01
Num of Std Step Trials= 20
Max Error Tol= 0.3
Flow Tol Ratio= 0.001
Split Flow NTrial= 30
Split Flow Tol= 0.02
Split Flow Ratio= 0.02
Log Output Level= 0
Friction Slope Method= 1
Unsteady Friction Slope Method= 2
Unsteady Bridges Friction Slope Method= 1
Parabolic Critical Depth
Global Vel Dist= 0 , 0 , 0
Global Log Level= 0
CheckData=True
Encroach Param=-1 ,0,0, 0
Computation Interval=0.1SEC
Output Interval=1SEC
Instantaneous Interval=Max Profile
Mapping Interval=1HOUR
Computation Time Step Use Courant=        0
Computation Time Step Use Time Series=    0
Computation Time Step Count To Double=0
Computation Time Step Max Doubling=0
Computation Time Step Max Halving=0
Computation Time Step Residence Courant=0
Run HTab= 0
Run UNet= 0
Run Sediment= 0
Run PostProcess= 0
Run WQNet= 0
Run RASMapper= 0
UNET Theta= 0
UNET Theta Warmup= 0
UNET ZTol= 0
UNET ZSATol= 0
UNET MxIter= 0
UNET Max Iter WO Improvement= 0
UNET MaxInSteps= 0
UNET DtIC= 0
UNET DtMin= 0
UNET MaxCRTS= 0
UNET WFStab= 0
UNET SFStab= 0
UNET WFX= 1
UNET SFX= 1
UNET Gravity=32.17405
UNET 1D Methodology=Finite Difference
UNET DSS MLevel= 1
UNET Pardiso=0
UNET DZMax Abort= 0
UNET Use Existing IB Tables= 0
UNET Froude Reduction=False
UNET Froude Limit= 0
UNET Froude Power= 0
UNET D1 Cores= 0
UNET WindReference=Eulerian
UNET WindDragFormulation=Hsu (1988)
UNET D2 Coriolis=0
UNET D2 Cores= 0
UNET D2 Theta= 1
UNET D2 Theta Warmup= 1
UNET D2 Z Tol= 0.01
UNET D2 Volume Tol= 0.01
UNET D2 Max Iterations= 20
UNET D2 Equation= 0
UNET D2 RampUpFraction=0.1
UNET D2 TimeSlices= 1
UNET D2 Turbulence Formulation=Non-Conservative (original)
UNET D2 Eddy Viscosity=0.3
UNET D2 Transverse Eddy Viscosity=0.1
UNET D2 Smagorinsky Mixing=0
UNET D2 BCVolumeCheck=0
UNET D2 Cores=0
UNET D2 SolverType=PARDISO (Direct)
UNET D2 Minimum Iterations= 3
UNET D2 Maximum Iterations= 30
UNET D2 Restart Number= 10
UNET D2 Relaxation Coeff=1.3
UNET D2 SOR Precondition Iterations= 10
UNET D2 ILUT Maximum Fill= 8
UNET D2 ILUT Tolerance=1E-08
UNET D2 Convergence Tolerance=0.00001
UNET D1D2 MaxIter= 0
UNET D1D2 ZTol=0.01
UNET D1D2 QTol=0.1
UNET D1D2 MinQTol=1
DSS File=dss
Write IC File= 0
Write IC File at Fixed DateTime=0
Write IC File at Sim End=0
Echo Input=False
Echo Parameters=False
Echo Output=False
Write Detailed= 0
HDF Write Warmup=0
HDF Write Time Slices=0
HDF Flush=0
HDF Compression= 1
HDF Chunk Size= 1
HDF Spatial Parts= 1
HDF Use Max Rows=0
HDF Fixed Rows= 1
Calibration Method= 0
Calibration Iterations= 20
Calibration Max Change=0.05
Calibration Tolerance=0.2
Calibration Maximum=1.5
Calibration Minimum=0.5
Calibration Optimization Method= 1
WQ AD Non Conservative
WQ ULTIMATE=-1
WQ Max Comp Step=1HOUR
WQ Output Interval=15MIN
WQ Output Selected Increments= 0
WQ Output face flow=0
WQ Output face velocity=0
WQ Output face area=0
WQ Output face dispersion=0
WQ Output cell volume=0
WQ Output cell surface area=0
WQ Output cell continuity=0
WQ Output cumulative cell continuity=0
WQ Output face conc=0
WQ Output face dconc_dx=0
WQ Output face courant=0
WQ Output face peclet=0
WQ Output face adv mass=0
WQ Output face disp mass=0
WQ Output cell mass=0
WQ Output cell source sink temp=0
WQ Output nsm pathways=0
WQ Output nsm derived pathways=0
WQ Create Restart=0
WQ Fixed Restart=0
WQ System Summary=0
WQ Write To DSS=0
Sorting and Armoring Iterations= 10
XS Update Threshold= 0.02
Bed Roughness Predictor= 0
Hydraulics Update Threshold= 0.02
Energy Slope Method= 1
Volume Change Method= 1
Sediment Retention Method= 0
Sediment TS Multiplier= 1
Warm Up Method= 0
XS Weighting Method= 0
Number of US Weighted Cross Sections= 1
Number of DS Weighted Cross Sections= 1
Upstream XS Weight=0
Main XS Weight=1
Downstream XS Weight=0
Number of DS XS's Weighted with US Boundary= 1
Upstream Boundary Weight= 1
Weight of XSs Associated with US Boundary= 0
Number of US XS's Weighted with DS Boundary= 1
Downstream Boundary Weight= 0.5
Weight of XSs Associated with DS Boundary= 0.5
Percentile Method= 0
Sediment Output Level= 3
Mass or Volume Output= 0
Output Increment Type= 1
Profile and TS Output Increment= 1
Transport Output Increment 1
XS Output Flag= 0
XS Output Increment= 10
Read HDF5 Sediment Hotstart= 0
Sediment Hotstart Type= 0
Write Gradation File= 0
Read Gradation Hotstart= 0
Write HDF5 File= 1
Write Binary Output= 1
Write DSS Sediment File= 0
DSS Sediment Output Type= 1
SV Curve= 0
Specific Gage Flag= 0
Subcell Erosion Methods= 0
Subcell Deposition Methods= 0
Advection Scheme= 1
Matrix Solver= 0
Implicit Weighting Factor= 1
Maximum Outer Loop Convergence Iterations= 5
Convergence Maximum Absolute= 0.001
Convergence RMSE= 0.0001
Grain Fractions Max Abs Error= 0.001
Max Subgrid Regions= 1
Max Subgrid Length Scale= 3.402823E+38
Initial Layer Thickness= 3.402823E+38
Min Layer Thickness= 3.402823E+38
Max Layer Thickness= 3.402823E+38
Number of Layers= 5

--- TURKEYRN.f01 (steady flow) ---

Flow Title=Flows
Program Version=6.30
Number of Profiles= 1
Profile Names=01pct
River Rch & RM=TURKEYRN,Main            ,25780
     359
River Rch & RM=TURKEYRN,Main            ,22184
     562
River Rch & RM=TURKEYRN,Main            ,21482
     654
River Rch & RM=TURKEYRN,Main            ,21257
     727
River Rch & RM=TURKEYRN,Main            ,18808
     868
River Rch & RM=TURKEYRN,Main            ,14065
    1050
River Rch & RM=TURKEYRN,Main            ,9013
    1240
River Rch & RM=TURKEYRN,Main            ,7616
    1650
Boundary for River Rch & Prof#=TURKEYRN,Main            , 1
Up Type= 0
Dn Type= 3
Dn Slope=0.00062
DSS Import GetInterval= 0
DSS Import GetPeak= 0
DSS Import FillOption= 0

--- TURKEYRN.g01 (geometry) ---

Geom Title=Geometry
Program Version=6.31

River Reach=TURKEYRN        ,Main
Reach XY= 30
2178285.75173731744257.607076287     2179430.133 744383.09800002
     2180132.265744176.2010000052180388.86800002744317.107999995
2181554.24200001744200.1529999972182145.79999998743361.005999997
2182633.39400002743326.6950000082183079.58100002      742725.522
     2184162.053742807.3359999952185067.41800003742396.519000009
2185376.99100003742447.9430000042185364.91399999 742262.65200001
2186072.08300003741725.150000036     2186389.639742023.877000019
2186375.53100003742318.8540000022187082.75600001742383.356000006
2187272.34000003742174.741999999      2187691.97742386.046000004
2188309.02599999742002.8150000132190045.78300002739869.263000011
2190819.39800002740305.2339999972192002.82900003739784.530000016
2193429.04100001739696.0189999942193740.58800004739292.958000019
2193885.53000005738010.743000016     2194287.075737497.622999996
2194055.25400002737259.9350000022194489.42099999736784.474000022
2194117.86599998736539.574000016     2194089.651      736100.198

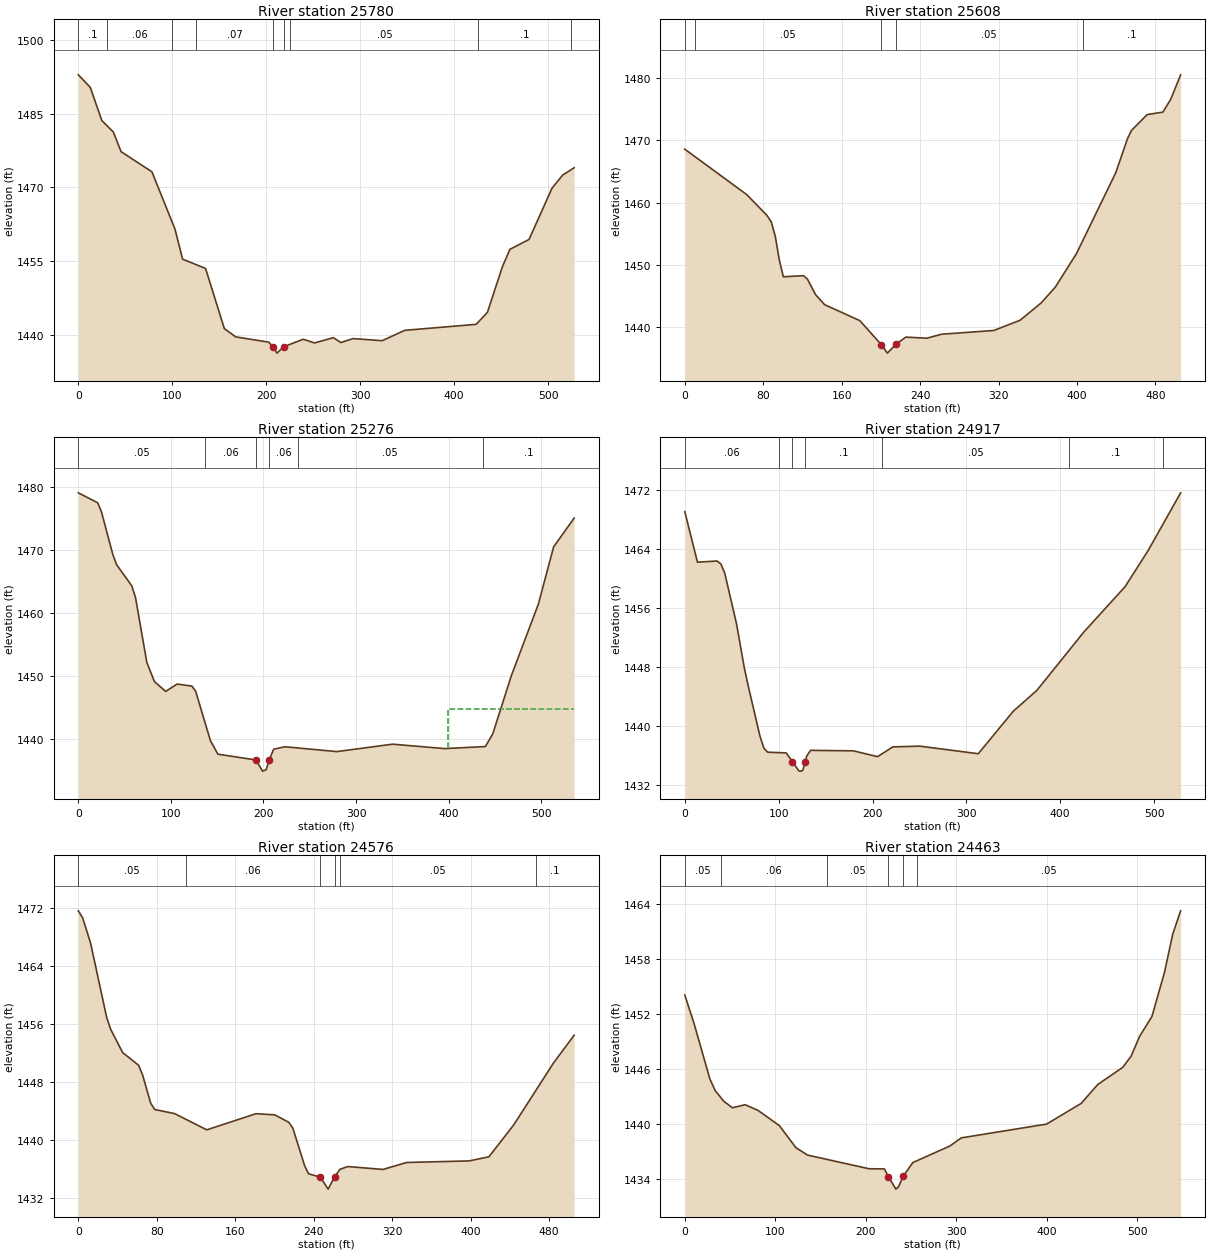
Type RM Length L Ch R = 1 ,25780   ,171.9,171.5,170.5
XS GIS Cut Line= 4
2178264.20605001744469.6291928372178291.05897143744346.779685725
2178299.11108654744008.691343111    2178323.7061743949.809871442
#Sta/Elev= 30
       0 1492.89    12.7 1490.34      25 1483.61    37.3 1481.25    45.5 1477.28
    78.3 1473.19   102.8 1461.58     111 1455.43   135.4 1453.55   155.4 1441.33
   167.4 1439.65   202.7 1438.56   207.4  1437.6   211.4 1436.34  218.531437.632
   239.4 1439.16   251.4 1438.41   271.4 1439.48   279.4 1438.49   292.5 1439.29
   323.4 1438.87   347.4 1440.97   423.4 1442.19   435.4 1444.63   451.4 1453.94
   459.4 1457.44   479.7 1459.44   504.1 1469.84   515.4 1472.51   527.7 1474.01
#Mann= 9 ,-1,0
       0      .1       0      30     .06       0     100     .05       0
  125.75     .07       0   207.4    .045       0  218.53     .07       0
  225.75     .05       0  425.75      .1       0  523.93     .05       0
Bank Sta=207.4,218.53
XS Rating Curve= 0 ,0
Exp/Cntr=0.3,0.1

Type RM Length L Ch R = 1 ,25608   ,328.7,332.5,331.5
XS GIS Cut Line= 4
2178425.36336428744454.8074428332178465.01267857 744292.66076429
2178445.50666513744104.6725502652178452.89523573  743955.1129143
#Sta/Elev= 30
       0 1468.58    63.2  1461.3      84 1457.93    88.2 1456.91    92.3 1454.61
    96.4 1450.82   100.5 1448.13   121.1  1448.3   125.2 1447.72   133.4 1445.26
   142.6 1443.66   178.5  1441.1   200.51437.242   206.6 1435.89  215.071437.276
   225.5 1438.46   246.8 1438.28   261.9 1438.92   315.2 1439.52   342.1 1441.17
   363.4 1443.93   377.9 1446.47   399.5 1451.85   439.5 1464.79   451.5 1470.26
   455.5 1471.57   471.6 1474.13   487.6 1474.52   495.6 1476.57   505.7  1480.5
#Mann= 5 ,-1,0
       0      .1       0      10     .05       0   200.5    .045       0
  215.07     .05       0  405.92      .1       0
Bank Sta=200.5,215.07
XS Rating Curve= 0 ,0
Exp/Cntr=0.3,0.1

Type RM Length L Ch R = 1 ,25276   ,353.9,358.1,359
XS GIS Cut Line= 4
2178732.15142858744481.776707115 2178711.1516223744377.104057439
2178738.66359999744026.3816999642178719.78165712743951.655271433
#Sta/Elev= 30
       0 1479.15      21 1477.56    25.1 1476.07    37.3 1469.33    41.4 1467.73
    57.7 1464.39    61.8  1462.5      74 1452.21    82.2 1449.17    94.4 1447.61
   106.7 1448.78   122.7 1448.45   126.7 1447.65   142.8 1439.75   150.8 1437.64
   191.81436.728     199 1434.95     203 1435.18   206.11436.722     211 1438.43
   223.1 1438.82   279.2 1438.05   339.4 1439.23   395.6 1438.53   439.7 1438.85
   447.7 1440.87   467.8 1450.13   496.9 1461.45   513.4 1470.56   535.6 1475.14
#Mann= 6 ,-1,0
       0     .05       0  136.76     .06       0   191.8    .045       0
   206.1     .06       0  236.76     .05       0  436.76      .1       0
#XS Ineff= 2 , 0
                          399.34         1444.89
Permanent Ineff=
       F       F
Bank Sta=191.8,206.1
XS Rating Curve= 0 ,0
Exp/Cntr=0.3,0.1

Type RM Length L Ch R = 1 ,24917   ,343.2,341.6,337.3
XS GIS Cut Line= 3
2179015.86280715744446.201742821    2179118.7423744080.823492826
2179149.42049286743935.312014286
#Sta/Elev= 30
       0 1469.07    13.5 1462.22    34.3 1462.38    38.5 1461.97    42.6 1460.72
    55.1 1453.87    63.4  1447.9    67.6 1445.42      80 1438.67    84.2    1437
    88.3 1436.44   108.1 1436.34   114.6 1435.17   121.6 1433.89   124.3 1433.87
   125.7 1433.99   128.3 1435.16   129.9 1435.91     134 1436.69   179.8 1436.62
   205.4 1435.83   221.6 1437.16   250.4 1437.26   312.7 1436.23   350.1 1442.01
   375.1 1444.82   425.3 1452.76   469.2 1458.91   493.7  1463.8   528.3 1471.63
#Mann= 7 ,-1,0
       0     .06       0     100      .1       0   114.6    .045       0
   128.3      .1       0     210     .05       0  409.59      .1       0
  509.59     .05       0
Bank Sta=114.6,128.3
XS Rating Curve= 0 ,0
Exp/Cntr=0.3,0.1

Type RM Length L Ch R = 1 ,24576   ,116.4,112.9,107.3
XS GIS Cut Line= 4
2179345.15702299744605.4468550582179375.44725546744458.510989505
2179356.01402857744405.2278500062179349.57450714744106.305778592
#Sta/Elev= 30
       0 1471.64     4.4 1470.67    12.5 1467.18    28.9 1456.92    32.9 1455.29
    45.2 1452.06    61.5  1450.3    65.6 1448.94    73.8 1445.07    77.9 1444.19
    98.3 1443.62     131 1441.38   181.2 1443.61   200.4 1443.45   214.8 1442.41
   218.8 1441.61   230.8 1436.43   234.8 1435.31   246.8 1434.84   254.8 1433.19
   261.3 1434.87   266.8 1435.92   274.8 1436.31   310.8 1435.91   334.8 1436.87
   398.8 1437.09   418.8 1437.66   444.1 1442.07   484.7 1450.63   505.7 1454.45
#Mann= 6 ,-1,0
       0     .05       0     110     .06       0   246.8    .045       0
   261.3     .06       0  266.74     .05       0  466.74      .1       0
Bank Sta=246.8,261.3
XS Rating Curve= 0 ,0
Exp/Cntr=0.3,0.1

Type RM Length L Ch R = 1 ,24463   ,66.5,66.6,66.7
XS GIS Cut Line= 6
2179562.01190762744577.6925717012179499.72791574744478.778022027
2179418.01644334744252.5169574222179413.44178002744210.224543425
2179421.19783716744175.3222862782179476.83862907744077.625814594
#Sta/Elev= 30
       0 1454.07    10.1 1451.01    27.8 1444.92    33.7 1443.65    43.1 1442.51
    52.6  1441.8    66.8 1442.13      81 1441.51   104.6 1439.85   122.8 1437.46
   135.6 1436.65   203.6 1435.16   220.7 1435.14     2251434.312   233.4 1432.94
   236.5 1433.22  241.37 1434.32   252.1 1435.83     293 1437.63   305.7 1438.52
     400 1440.02   438.2 1442.27   456.6 1444.33   484.2  1446.2   493.5 1447.42
   502.7 1449.55   516.5 1451.74   530.3 1456.52   539.5  1460.7   548.2 1463.24
#Mann= 6 ,-1,0
       0     .05       0      40     .06       0  156.89     .05       0
     225    .045       0  241.37     .06       0  256.89     .05       0
Bank Sta=225,241.37
XS Rating Curve= 0 ,0
Exp/Cntr=0.3,0.1

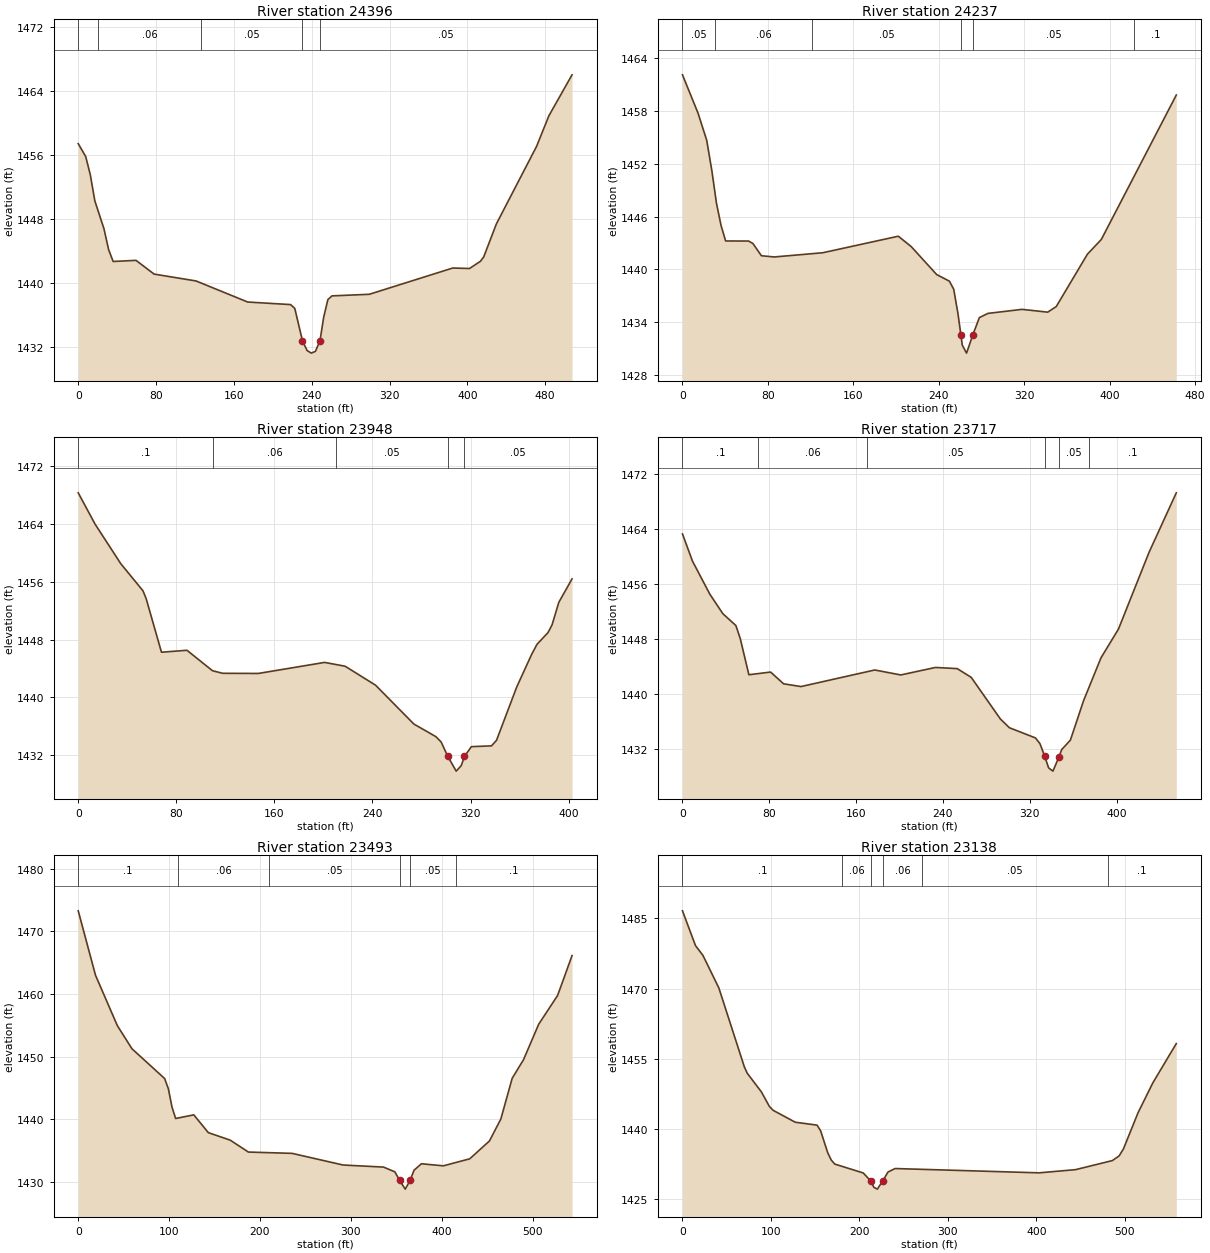
Type RM Length L Ch R = 1 ,24396   ,154.6,159.4,162.2
XS GIS Cut Line= 6
 2179615.9591873744559.733891914 2179575.9738597744494.752092244
 2179494.2623873744268.4910276392179489.68772398744226.198613642
2179497.44378112744191.2963564952179553.08457303744093.599884811
#Sta/Elev= 30
       0 1457.41     7.7 1455.79    12.4 1453.52    17.1 1450.23    26.5 1446.73
    31.2 1444.15    35.9 1442.65    59.4 1442.79      78 1441.07   121.1 1440.21
   174.2 1437.57   218.3 1437.25   222.6 1436.77   230.5 1432.71   235.3 1431.49
   239.6 1431.17   243.8 1431.39  248.52 1432.72   252.3 1435.66   256.6 1437.87
   260.8 1438.34   299.2 1438.54     385 1441.83   402.2 1441.77   413.4 1442.67
   416.8 1443.22   429.8 1447.35   471.2 1457.08   483.8  1460.9   507.6 1466.03
#Mann= 5 ,-1,0
       0     .05       0      20     .06       0   126.3     .05       0
   230.5    .045       0  248.52     .05       0
Bank Sta=230.5,248.52
XS Rating Curve= 0 ,0
Exp/Cntr=0.3,0.1

Type RM Length L Ch R = 1 ,24237   ,289.8,289.2,284
XS GIS Cut Line= 4
2179672.09547222744562.7488656512179649.35793631744505.694268934
2179655.15088064744204.0642680632179617.00130714744112.421685741
#Sta/Elev= 30
       0 1462.14    14.6 1457.77    22.7 1454.69    27.5 1451.24    31.8 1447.55
    36.1 1445.01    40.4 1443.24    61.9 1443.23    65.9 1442.96    73.9 1441.56
    85.9 1441.42   131.4  1441.9   202.1 1443.78   214.1 1442.61     238 1439.42
     250 1438.66     254 1437.74     258 1434.94  260.671432.585     262 1431.39
     266 1430.48     2721432.597     278 1434.52     286    1435     318 1435.46
     342 1435.14     350 1435.78   379.2 1441.74   392.2 1443.41   462.4 1459.84
#Mann= 6 ,-1,0
       0     .05       0      30     .06       0  121.42     .05       0
  260.67    .045       0     272     .05       0   423.1      .1       0
Bank Sta=260.67,272
XS Rating Curve= 0 ,0
Exp/Cntr=0.3,0.1

Type RM Length L Ch R = 1 ,23948   ,229.3,231.2,232.3
XS GIS Cut Line= 3
2179988.11877328744546.4571986312179925.53364872744327.385769937
2179884.26402023744157.350493891
#Sta/Elev= 30
       0 1468.34    13.8 1463.99    34.6 1458.55    52.8 1454.77    55.4 1453.69
    67.9 1446.26    88.7 1446.53   109.5  1443.7   117.8 1443.34   146.9 1443.32
     201 1444.85   217.7 1444.32   242.5  1441.7   273.8 1436.31   291.8 1434.56
     296 1433.83   301.4 1431.85   308.3 1429.79   312.4 1430.55  315.06 1431.83
   320.7 1433.18   337.1 1433.29   341.2 1434.06   357.7 1441.45   369.9 1445.98
   374.2 1447.35   383.2 1448.98   386.5 1450.05     392 1453.17   402.8 1456.42
#Mann= 5 ,-1,0
       0      .1       0     110     .06       0     210     .05       0
   301.4    .045       0  315.06     .05       0
Bank Sta=301.4,315.06
XS Rating Curve= 0 ,0
Exp/Cntr=0.3,0.1

Type RM Length L Ch R = 1 ,23717   ,222.3,223.1,219.6
XS GIS Cut Line= 3
2180131.73223458744518.3443860582180123.85026935744203.371414145
2180107.93176877744064.243575817
#Sta/Elev= 30
       0 1463.25     9.2  1459.3    25.2 1454.49    37.2 1451.65    49.2 1449.93
    53.2 1448.06    61.2 1442.77    81.2 1443.16    93.2 1441.45   109.2 1441.05
   177.2 1443.46   201.2 1442.74   233.2 1443.83   253.2 1443.66   266.1 1442.39
     293 1436.33   301.3 1435.06   325.3 1433.58   329.4 1432.76  333.881430.903
   337.4 1429.23   341.4 1428.75  347.051430.841   349.5 1431.89   357.5 1433.26
   369.6 1438.98   385.7 1445.23   401.8 1449.41     430 1460.58   455.1 1469.23
#Mann= 6 ,-1,0
       0      .1       0      70     .06       0     170     .05       0
  333.88    .045       0  347.05     .05       0  375.07      .1       0
Bank Sta=333.88,347.05
XS Rating Curve= 0 ,0
Exp/Cntr=0.3,0.1

Type RM Length L Ch R = 1 ,23493   ,349,355.2,352.1
XS GIS Cut Line= 3
2180287.90902809744556.1341088472180308.63975757744231.009253638
2180247.94461947744021.953969734
#Sta/Elev= 30
       0  1473.3      19 1463.02      43 1454.98    59.1 1451.28    95.1 1446.52
    99.2 1444.89   103.2 1441.97   107.2 1440.14   127.2 1440.72   143.2 1437.88
   167.3 1436.68   187.3 1434.78   235.4 1434.57   291.5 1432.71     336 1432.38
   348.5 1431.62   353.71430.269   359.9 1428.86  365.271430.258   369.6 1431.88
   377.7 1432.91   401.9 1432.58   430.9  1433.7   452.6 1436.55   465.1 1440.04
   477.6 1446.55   490.1 1449.53   506.8 1455.19   527.6 1459.78   543.5 1466.15
#Mann= 6 ,-1,0
       0      .1       0     110     .06       0     210     .05       0
   353.7    .045       0  365.27     .05       0  415.79      .1       0
Bank Sta=353.7,365.27
XS Rating Curve= 0 ,0
Exp/Cntr=0.3,0.1

Type RM Length L Ch R = 1 ,23138   ,279.4,280.8,280.1
XS GIS Cut Line= 4
2180593.33018255744515.2454920422180552.39147283744380.651043945
2180545.64442064744280.4841587292180457.64477144743975.740694605
#Sta/Elev= 30
       0 1486.61    14.7 1479.18    23.1  1477.1    41.1 1470.14    69.9 1453.29
    73.2 1451.91    89.1 1447.95    98.3  1444.8   102.5 1443.98   127.5 1441.44
   152.2 1440.81   156.2 1439.59   164.2 1434.92   168.2 1433.35   172.2 1432.49
   204.4 1430.59  212.961428.851   216.3 1427.54   220.3 1427.14  226.161428.826
   232.4  1430.8   240.4 1431.54   403.2 1430.62   444.4  1431.3     486 1433.24
   493.7 1434.25   498.5 1435.72   515.1 1443.48   531.8 1449.86   558.3 1458.24
#Mann= 6 ,-1,0
       0      .1       0  180.68     .06       0  212.96    .045       0
  226.16     .06       0  271.08     .05       0  481.08      .1       0
Bank Sta=212.96,226.16
XS Rating Curve= 0 ,0
Exp/Cntr=0.3,0.1

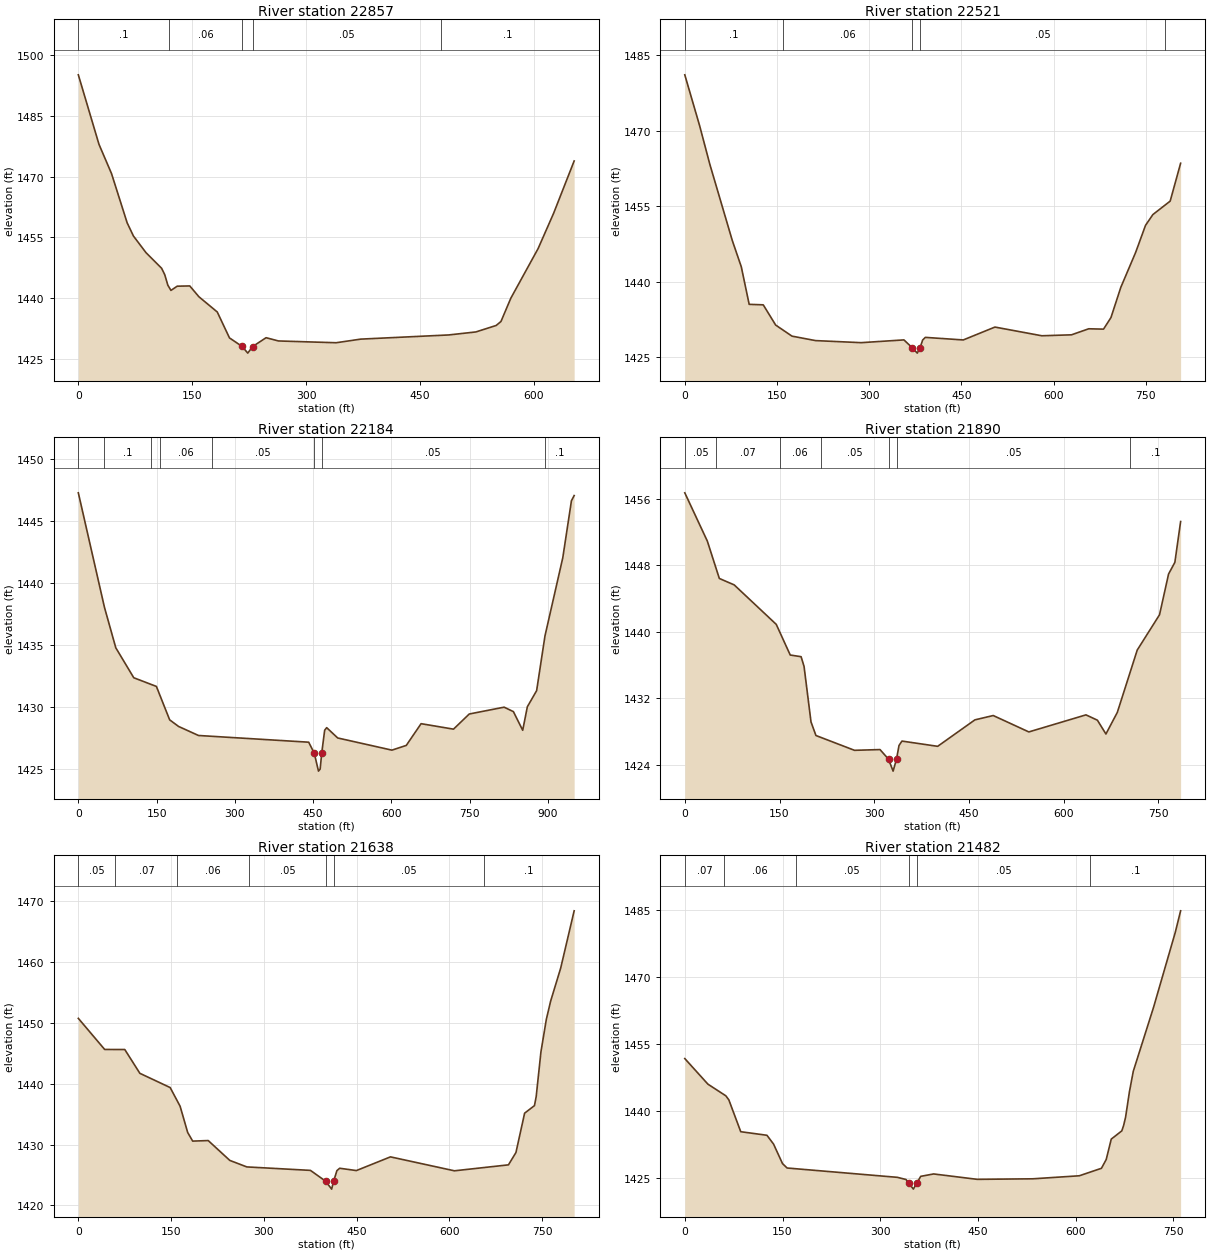
Type RM Length L Ch R = 1 ,22857   ,338.9,336.3,332.1
XS GIS Cut Line= 4
2180851.57141269744459.5997222012180815.23563159744313.862774096
2180791.60797618744067.7971745832180631.98452001743868.081810512
#Sta/Elev= 30
       0 1495.09    27.2 1477.96    43.7 1470.76    64.3 1458.62    72.6 1455.36
    89.1 1451.27   109.7 1447.41   113.8 1445.85   117.9 1443.25     122 1441.96
   130.3    1443   146.8 1443.06   158.9 1440.38     183 1436.64   199.1 1430.25
   215.8 1428.14   223.2  1426.5  229.531428.114   247.3  1430.3   263.6  1429.5
   339.7 1429.06   371.9 1429.95   487.8 1430.98   523.6 1431.72   550.3 1433.31
   556.7  1434.3   569.7 1440.04   605.6 1452.26   626.1 1460.99   653.1 1473.86
#Mann= 5 ,-1,0
       0      .1       0     120     .06       0   215.8    .045       0
  229.53     .05       0   477.4      .1       0
Bank Sta=215.8,229.53
XS Rating Curve= 0 ,0
Exp/Cntr=0.3,0.1

Type RM Length L Ch R = 1 ,22521   ,325.9,337.5,343.6
XS GIS Cut Line= 5
 2181106.9542857744484.8295079272181195.49787766744324.635075685
2181111.47392527744127.5019566142181072.04566667744042.988857125
2181046.21450796743728.209896815
#Sta/Elev= 30
       0 1481.15    24.2    1471    40.7 1463.37    77.3 1448.19    91.9 1442.98
   104.7 1435.52   127.6 1435.42   147.8  1431.4   174.3  1429.2   212.6 1428.31
   286.8  1427.9   356.4 1428.45     3701426.875   378.1 1425.82   382.5 1426.85
   386.8 1428.41   391.2 1428.95   452.9 1428.44   504.4    1431   580.7 1429.27
   628.9 1429.46     657 1430.66     681 1430.59   693.1 1432.89   709.1 1438.89
   733.2 1445.83   749.3 1451.22   761.3 1453.37   789.4 1456.04   806.4 1463.57
#Mann= 5 ,-1,0
       0      .1       0     160     .06       0     370    .045       0
   382.5     .05       0  780.59      .1       0
Bank Sta=370,382.5
XS Rating Curve= 0 ,0
Exp/Cntr=0.3,0.1

Type RM Length L Ch R = 1 ,22184   ,310.3,293.9,279.1
XS GIS Cut Line= 5
2181288.84956349744589.8349761952181338.76948879744451.748234429
2181448.81623016744140.6603174582181493.89063167743979.921424852
2181359.66866667743704.539468253
#Sta/Elev= 30
       0 1447.25      50 1438.04    71.8 1434.77   106.2 1432.36   149.6 1431.66
     175 1428.97     192 1428.44   230.2 1427.71   441.4 1427.17  452.081426.284
   460.2 1424.84   463.4 1425.01   466.41426.287     472 1428.13   475.9 1428.34
     497 1427.51   600.9 1426.53   628.4 1426.91   656.8 1428.66   718.9 1428.22
   749.1 1429.44   815.9 1429.99   833.7 1429.63   851.5 1428.13   860.4 1430.02
   878.2 1431.32   894.2 1435.73   928.3 1442.02   944.9 1446.61   950.1 1447.03
#Mann= 8 ,-1,0
       0     .05       0      50      .1       0     140     .05       0
  156.83     .06       0  256.83     .05       0  452.08    .045       0
   466.4     .05       0  893.75      .1       0
Bank Sta=452.08,466.4
XS Rating Curve= 0 ,0
Exp/Cntr=0.3,0.1

Type RM Length L Ch R = 1 ,21890   ,245.7,251.4,254.3
XS GIS Cut Line= 4
2181850.13099205744275.2592222242181755.65756027744127.501956614
2181525.79767459743985.595952375     2181368.751      743684.275
#Sta/Elev= 30
       0 1456.71    35.7 1450.91    54.7 1446.42    78.2 1445.65   144.9  1440.9
     167 1437.22   184.2 1437.02   188.9 1435.85   199.9 1429.18   207.7 1427.55
   268.8 1425.77   309.2 1425.86   322.71424.702   329.9 1423.27  335.321424.709
   339.3 1426.36     344 1426.88   400.5 1426.25   459.5 1429.43   488.5 1429.95
   544.9 1427.98   635.4 1430.03   653.5 1429.39     667 1427.73     685 1430.32
   716.6 1437.82   751.9 1442.06   766.2 1446.95   776.2 1448.36   785.3 1453.26
#Mann= 7 ,-1,0
       0     .05       0      50     .07       0     150     .06       0
  215.38     .05       0   322.7    .045       0  335.32     .05       0
  705.51      .1       0
Bank Sta=322.7,335.32
XS Rating Curve= 0 ,0
Exp/Cntr=0.3,0.1

Type RM Length L Ch R = 1 ,21638   ,158,156.3,154.5
XS GIS Cut Line= 4
2181926.49200793744211.1245872922181889.72704766744008.062246013
 2181692.1009809743744.0080200632181555.05688098743516.646111089
#Sta/Elev= 30
       0 1450.73    42.6 1445.62    75.1 1445.61    99.5  1441.7   148.5 1439.36
   164.6 1436.28   176.8 1431.98   184.9 1430.56     210 1430.65   244.9 1427.39
   272.4 1426.32   375.3 1425.75   399.8 1423.98   409.6 1422.67  412.731423.953
   418.1 1425.71   422.6  1426.1   449.6 1425.72   504.7 1427.97   608.1 1425.68
   695.5 1426.66   707.6 1428.69   721.6 1435.15   737.5 1436.39   740.3 1437.86
     748 1445.23   756.7 1450.56   763.7 1453.57   779.9 1458.98   801.7  1468.4
#Mann= 7 ,-1,0
       0     .05       0      60     .07       0     160     .06       0
  276.36     .05       0   399.8    .045       0  412.73     .05       0
  656.18      .1       0
Bank Sta=399.8,412.73
XS Rating Curve= 0 ,0
Exp/Cntr=0.3,0.1

Type RM Length L Ch R = 1 ,21482   ,162,176.9,182.3
XS GIS Cut Line= 3
2182171.21331922743937.6560440832181968.20250794743824.563162271
     2181577.472      743468.209
#Sta/Elev= 30
       0 1451.65    35.5 1445.92      63 1443.31    67.6 1442.41    85.9 1435.27
   126.1 1434.47   136.3 1432.49     150 1428.13   157.1 1427.14   326.4 1425.05
   339.6 1424.56   343.8  1423.8   350.9 1422.41  356.211423.785   362.2 1425.27
     382 1425.81     449  1424.6   534.2 1424.72   605.7  1425.4   639.7 1427.08
     647 1429.06   654.7 1433.61   670.9 1435.46   673.7 1436.67   676.7 1438.52
   682.6 1444.21   688.5 1448.79   719.7 1463.16     753 1479.92   761.2 1484.74
#Mann= 6 ,-1,0
       0     .07       0      60     .06       0     170     .05       0
   343.8    .045       0  356.21     .05       0  622.39      .1       0
Bank Sta=343.8,356.21
XS Rating Curve= 0 ,0
Exp/Cntr=0.3,0.1

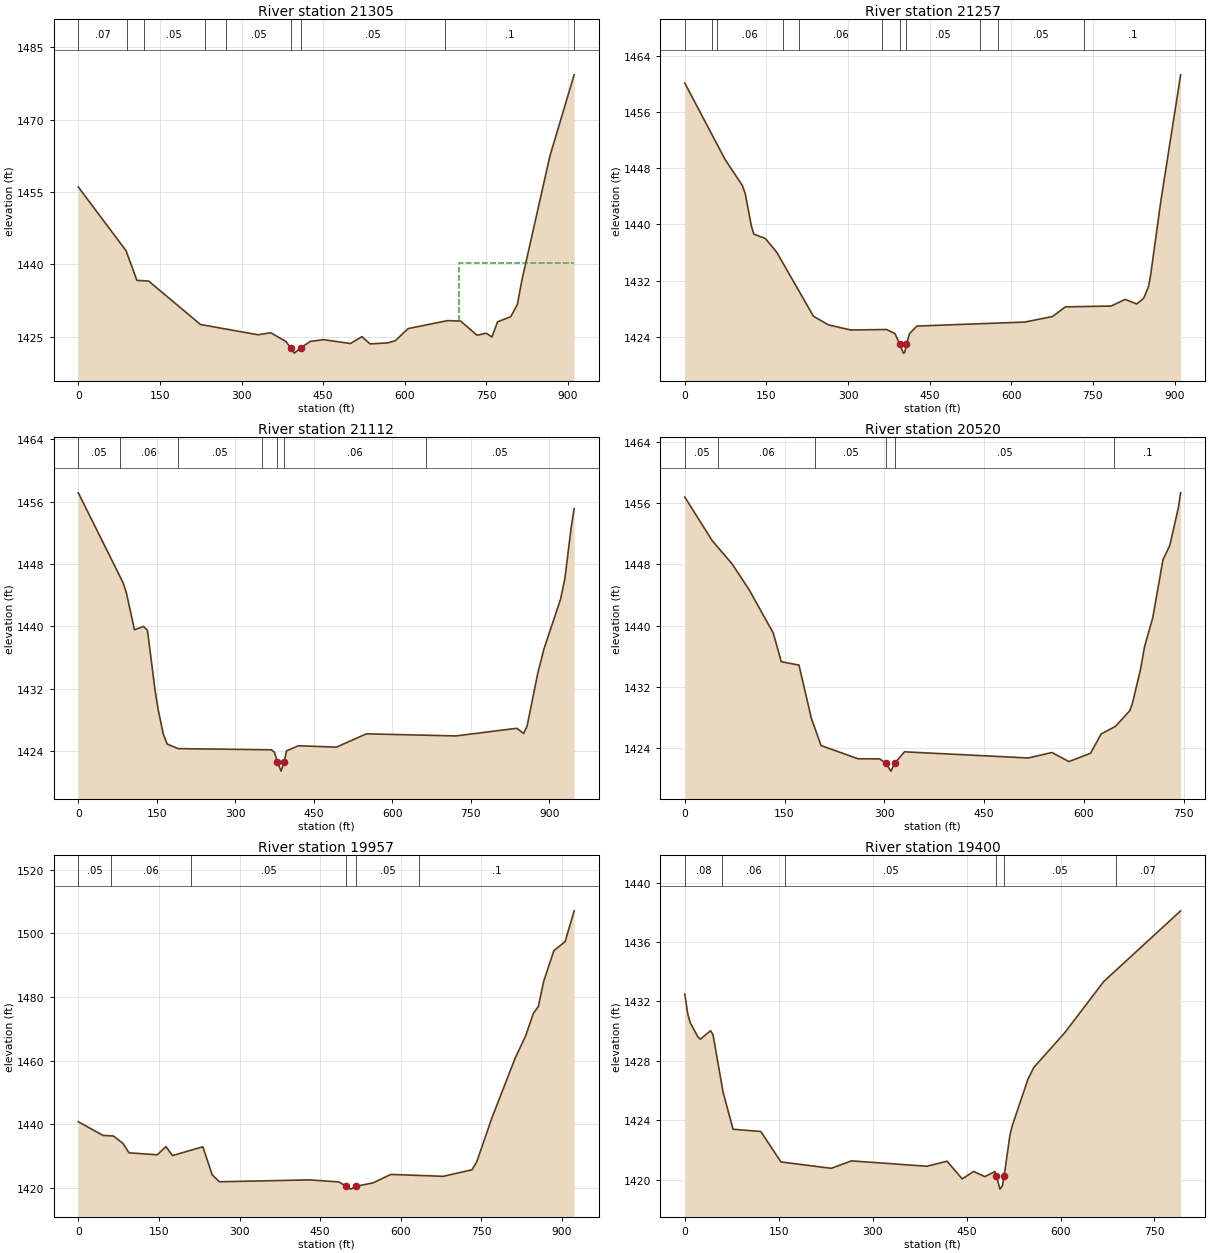
Type RM Length L Ch R = 1 ,21305   ,54.2,47.6,47.3
XS GIS Cut Line= 6
2182210.41198411743914.6517460362182049.19257937 743776.81120637
2181891.65580791743472.6267731312181822.71307774743363.826527087
2181747.30696662743300.2699477142181626.41389682 743345.43496826
#Sta/Elev= 30
       0 1456.04    87.7 1442.85   107.6 1436.72   129.2 1436.57   224.5 1427.58
   330.3 1425.45   353.5 1425.87   381.8 1424.04  390.051422.754     397 1421.65
   408.5 1422.73   426.3 1424.07   450.4 1424.44     500 1423.64   521.2 1425.07
   536.1 1423.56   568.6 1423.77   582.4 1424.21     606 1426.73   678.5 1428.38
   702.5 1428.29   732.6 1425.36   749.6 1425.77     760 1424.99   770.5 1428.14
   794.6 1429.19   806.8 1431.74   815.3 1436.83   866.6 1462.46   911.1 1479.27
#Mann= 9 ,-1,0
       0     .07       0      90     .06       0     120     .05       0
  232.11     .06       0  272.11     .05       0  390.05    .045       0
   408.5     .05       0  674.67      .1       0  911.15     .05       0
#XS Ineff= 2 , 0
                          699.67         1440.32
Permanent Ineff=
       F       F
Bank Sta=390.05,408.5
XS Rating Curve= 0 ,0
Exp/Cntr=0.3,0.1

Type RM Length L Ch R = 1 ,21257   ,145,145.5,143
XS GIS Cut Line= 6
2182252.54799109743893.5219265962182091.32858635743755.681386929
2181933.79181488 743451.496953692181864.84908471743342.696707646
2181789.44297359743279.1401282742181668.54990379 743324.30514882
#Sta/Elev= 30
       0  1460.1    74.2  1449.2   105.7 1445.54   111.2 1444.33   122.5 1439.72
   126.8 1438.61     148 1437.99   168.9 1436.03   236.4 1426.93   263.8  1425.7
     305 1424.97   370.6 1425.04   386.1 1424.47   395.1 1422.94   401.6 1421.68
   404.1 1421.75  407.251422.925   413.1 1424.47   426.6 1425.53   624.9  1426.1
   675.8 1426.89   699.2 1428.26   783.4 1428.38   809.1 1429.32   830.4 1428.68
   843.2 1429.49   851.8 1431.07   855.8 1432.68   874.8 1443.33   911.1 1461.27
#Mann= 11 ,-1,0
       0     .05       0      50     .07       0      60     .06       0
     180     .05       0     210     .06       0  362.11     .05       0
   395.1    .045       0  407.25     .05       0  542.11     .06       0
  574.67     .05       0  733.48      .1       0
Bank Sta=395.1,407.25
XS Rating Curve= 0 ,0
Exp/Cntr=0.3,0.1

Type RM Length L Ch R = 1 ,21112   ,585.7,592.1,589.1
XS GIS Cut Line= 5
2182284.44930413743826.3265196452182239.77053113743703.235658702
2182002.28992627743343.5267884982181947.15072026743282.008057066
2181934.95641457742979.450564006
#Sta/Elev= 30
       0 1457.13    85.4  1445.6    91.7 1444.32   107.3 1439.54   124.6 1439.97
   132.1 1439.46   146.6 1431.79   152.4 1429.33   162.2 1426.19   169.7 1424.87
   190.9 1424.28   368.9 1424.13   374.7 1423.81   380.4 1422.59   387.4 1421.39
   393.21422.576   397.8 1423.99   420.6 1424.65   493.2 1424.47   550.4 1426.18
   721.4 1425.91   837.6 1426.89   850.9 1426.23   857.6 1427.21   877.6 1433.87
   889.6 1437.06   921.5 1443.48   929.7 1446.15   941.7 1452.68   947.4  1455.1
#Mann= 7 ,-1,0
       0     .05       0      80     .06       0  190.95     .05       0
  350.95     .06       0   380.4    .045       0   393.2     .06       0
  664.59     .05       0
Bank Sta=380.4,393.2
XS Rating Curve= 0 ,0
Exp/Cntr=0.3,0.1

Type RM Length L Ch R = 1 ,20520   ,563.4,562.9,526
XS GIS Cut Line= 4
2182728.47404759743592.6086746072182604.78217307743482.321844561
2182357.11731743743069.1749761642182320.95800793742977.966801596
#Sta/Elev= 30
       0 1456.81    41.2 1451.11    71.3 1448.05    96.9 1444.66     133 1439.02
   145.1 1435.26   171.7 1434.82   190.2 1427.88   204.9 1424.29   260.3 1422.56
     293 1422.54   302.3 1421.99   309.9 1420.94  315.621421.963   330.3 1423.47
   516.6 1422.66   551.9 1423.38   577.5 1422.19   610.1 1423.28   625.9  1425.8
   647.4 1426.79   668.9 1428.83   672.8 1429.73   685.1 1434.21   691.3 1437.25
   703.6 1441.02     719 1448.62   729.2 1450.47   742.1 1455.43   745.5 1457.37
#Mann= 6 ,-1,0
       0     .05       0      50     .06       0  195.72     .05       0
   302.3    .045       0  315.62     .05       0  645.72      .1       0
Bank Sta=302.3,315.62
XS Rating Curve= 0 ,0
Exp/Cntr=0.3,0.1

Type RM Length L Ch R = 1 ,19957   ,541.3,557.4,565.8
XS GIS Cut Line= 4
2183016.89524601743374.5587698572182985.04441914743154.843876269
2182645.59766666 743005.03992857     2182464.363      742729.618
#Sta/Elev= 30
       0 1440.83    45.9 1436.53    65.4 1436.34      83 1434.01    94.4 1431.06
   146.9 1430.44   163.1 1433.02   175.2 1430.19   231.7 1432.96   249.2 1424.14
   262.3 1421.97   430.2 1422.56   484.8 1421.92   498.4 1420.59   507.2 1419.66
  517.571420.581   548.5 1421.62   581.5 1424.28   679.1 1423.68   732.6 1425.74
   741.3 1428.19     770  1442.2   813.1 1460.87   832.3 1467.73   846.7 1474.82
   856.2 1477.08   865.8  1484.8     885 1494.57   905.9 1497.38   922.7 1507.06
#Mann= 6 ,-1,0
       0     .05       0      60     .06       0     210     .05       0
   498.4    .045       0  517.57     .05       0  633.04      .1       0
Bank Sta=498.4,517.57
XS Rating Curve= 0 ,0
Exp/Cntr=0.3,0.1

Type RM Length L Ch R = 1 ,19400   ,118.2,117.4,116
XS GIS Cut Line= 3
2183144.47448265743225.9410667542183089.94813492 742680.67590475
2182947.11020637742483.042992065
#Sta/Elev= 30
       0  1432.5     4.8 1431.15     8.8 1430.56    20.9 1429.62    24.9 1429.46
      41 1430.03      45 1429.78    61.1  1425.9    77.1  1423.4   121.4 1423.25
   153.5  1421.2   233.9 1420.77   266.1 1421.27   386.7 1420.91   418.8 1421.25
     443 1420.06   461.4 1420.56   479.1 1420.21   495.2 1420.55   497.51420.272
   503.3 1419.37   507.3 1419.59  510.021420.272   519.3 1423.02   523.1 1423.66
     548 1426.77   557.2 1427.55   606.6 1429.89   669.2 1433.35   791.8  1438.1
#Mann= 6 ,-1,0
       0     .08       0      60     .06       0     160     .05       0
   497.5    .045       0  510.02     .05       0  687.98     .07       0
Bank Sta=497.5,510.02
XS Rating Curve= 0 ,0
Exp/Cntr=0.3,0.1

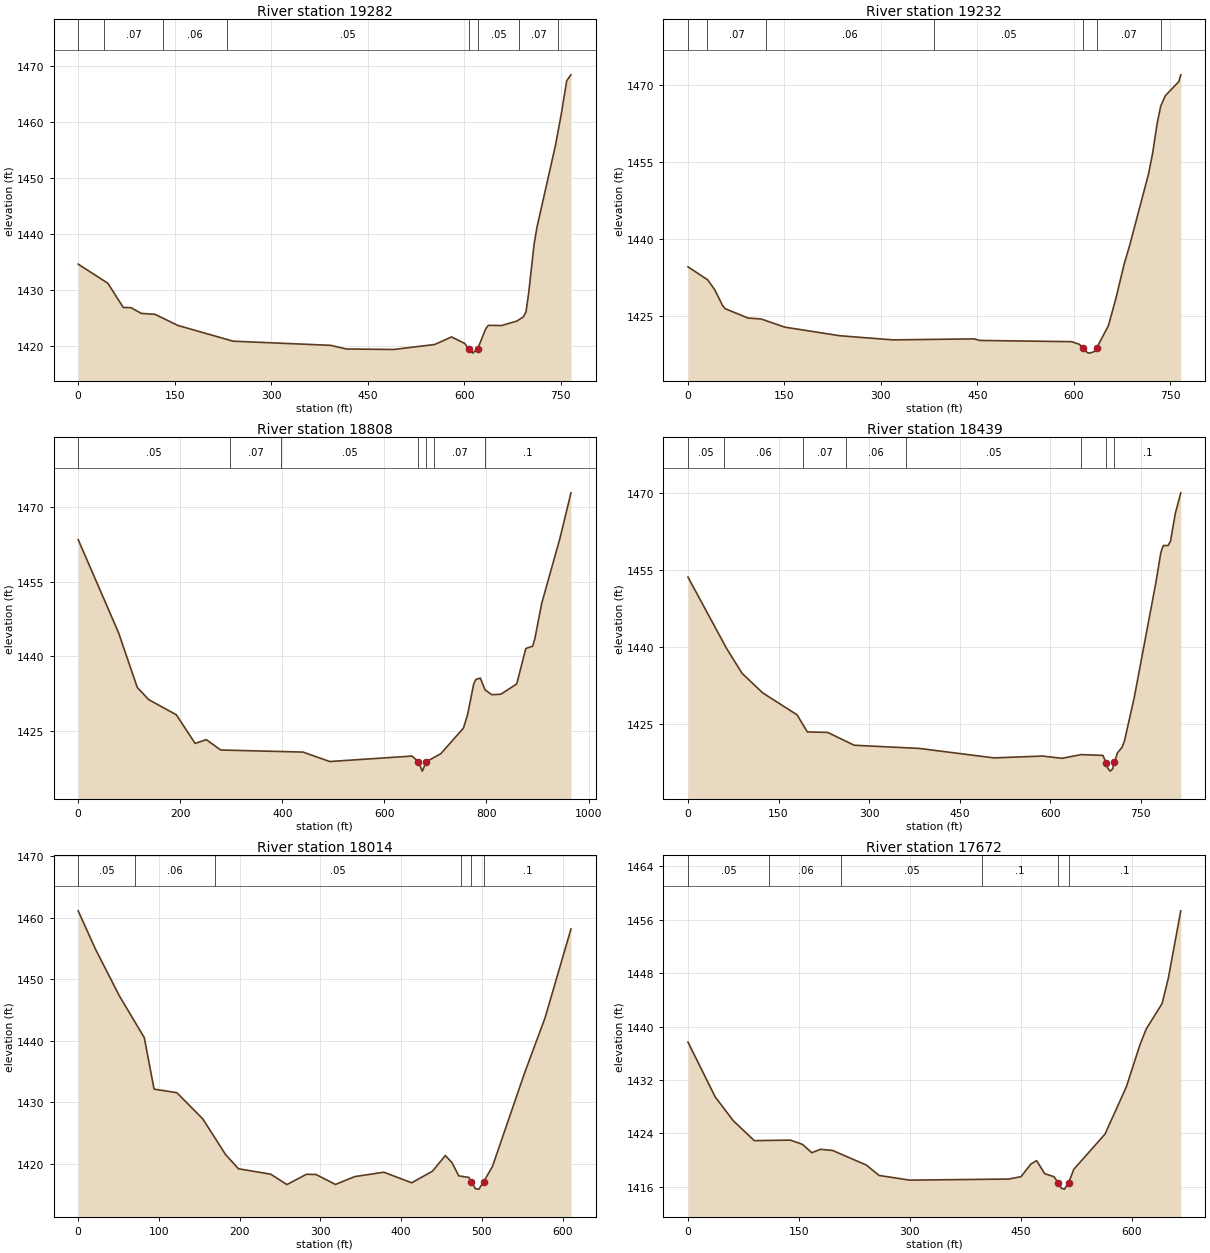
Type RM Length L Ch R = 1 ,19282   ,49.6,50.5,50.8
XS GIS Cut Line= 4
2183310.31429231743299.2680196572183311.07912347743187.428919946
2183197.33710183742655.4465910632183232.27840342 742550.86149586
#Sta/Elev= 30
       0 1434.59    46.1 1431.18    70.1 1426.86    82.1 1426.82    98.1  1425.8
   119.6 1425.63     155 1423.65   240.9 1420.84   392.5  1420.1   416.8 1419.45
   490.5 1419.36   554.3 1420.25   580.4  1421.6   600.9 1420.44   606.91419.494
   613.2 1418.71  621.161419.486   633.6 1423.06   637.7 1423.67   658.2 1423.63
     682 1424.43     692 1425.17   696.2 1426.07   700.4 1429.48   708.8 1438.15
   713.1 1441.09   742.1 1455.83     751 1461.32   759.5  1467.3   766.1 1468.36
#Mann= 8 ,-1,0
       0     .05       0      40     .07       0  131.84     .06       0
  231.84     .05       0   606.9    .045       0  621.16     .05       0
  685.85     .07       0  745.85     .06       0
Bank Sta=606.9,621.16
XS Rating Curve= 0 ,0
Exp/Cntr=0.3,0.1

Type RM Length L Ch R = 1 ,19232   ,410.7,423.4,422.6
XS GIS Cut Line= 4
2183358.84222222743290.7681428752183359.60705338743178.929043164
2183245.86503174742646.9467142812183280.80633333742542.361619078
#Sta/Elev= 30
       0 1434.58    30.7 1432.04    41.6 1430.12    53.6 1427.09    57.6 1426.44
    93.6  1424.6   113.6 1424.43   150.4 1422.84   236.3 1421.16   318.4 1420.36
     445 1420.55   453.5 1420.25   596.3 1420.01   608.6 1419.49   614.3 1418.75
   620.8 1417.88   624.9 1417.78   631.8 1418.09   635.2 1418.75   653.6 1423.12
   665.4  1428.5     678 1435.07   686.7 1438.77     716 1452.68   722.3 1456.65
   729.4 1462.49   734.9 1465.84   742.1 1467.89   763.1 1470.63   766.1 1471.95
#Mann= 7 ,-1,0
       0     .05       0      30     .07       0  121.84     .06       0
  381.84     .05       0   614.3    .045       0   635.2     .07       0
  735.85     .06       0
Bank Sta=614.3,635.2
XS Rating Curve= 0 ,0
Exp/Cntr=0.3,0.1

Type RM Length L Ch R = 1 ,18808   ,368.3,369.6,365
XS GIS Cut Line= 4
2183512.29502197743458.3194831672183567.55430093743206.390897669
2183631.47246059742690.2285831292183713.70836508742521.675746052
#Sta/Elev= 30
       0  1463.5      79 1444.81   115.8 1433.77     138 1431.33   192.3 1428.27
   229.2 1422.51     251 1423.27   279.3 1421.19   440.5 1420.77   492.9 1418.87
   654.2 1419.97   666.81418.817   674.3 1416.94  682.131418.836   710.6 1420.45
   754.9 1425.59     763 1428.29     775 1434.45   779.3 1435.38   788.1 1435.64
     797 1433.31   810.3 1432.31   828.1  1432.4   859.3 1434.47   877.1  1441.6
   890.5 1442.06   894.9 1443.59   908.3  1450.7   943.9 1463.72   965.6  1472.9
#Mann= 7 ,-1,0
       0     .05       0  297.92     .07       0  397.92     .05       0
   666.8    .045       0  682.13     .05       0  697.92     .07       0
  798.02      .1       0
Bank Sta=666.8,682.13
XS Rating Curve= 0 ,0
Exp/Cntr=0.3,0.1

Type RM Length L Ch R = 1 ,18439   ,424.2,424.4,416.4
XS GIS Cut Line= 3
2184138.57645282743332.6119112892183948.87758296743182.825108401
2183939.86664688742608.223091679
#Sta/Elev= 30
       0 1453.57      64  1439.7    89.7 1434.86   123.8 1431.08   180.7 1426.81
   197.8 1423.49   231.5 1423.39   275.4  1420.9   383.4 1420.28   506.8 1418.44
   587.4  1418.8   619.4 1418.36   651.4 1419.08   687.4 1418.93   692.71417.536
   695.4 1416.44   699.4 1415.87   703.4 1416.28  706.46 1417.55   711.4  1419.4
   719.4 1420.54   723.4 1421.87   739.4 1430.22   775.1 1452.48   783.4 1458.36
   787.4  1459.7   795.4 1459.72   799.4 1460.55   807.4 1465.97   816.4 1469.95
#Mann= 8 ,-1,0
       0     .05       0      60     .06       0     190     .07       0
  261.71     .06       0  361.71     .05       0  651.71      .1       0
   692.7    .045       0  706.46      .1       0
Bank Sta=692.7,706.46
XS Rating Curve= 0 ,0
Exp/Cntr=0.3,0.1

Type RM Length L Ch R = 1 ,18014   ,342.1,342.6,341.3
XS GIS Cut Line= 4
2184363.46363825743238.4818265822184343.50180875743070.143979259
 2184333.0661433742785.7948566232184290.00548169742635.551806812
#Sta/Elev= 30
       0  1461.1    21.5 1454.85    50.9  1447.3    81.9 1440.47      94 1432.11
   122.2 1431.53   154.4 1427.26   182.5 1421.48   198.5 1419.16   238.5 1418.28
   258.5 1416.59   282.6 1418.26   294.6 1418.23   318.6 1416.61   342.6 1417.89
   378.6  1418.6     413 1416.88   438.7 1418.76   454.7 1421.31     463 1420.16
   471.3 1418.01   483.8 1417.75  486.921417.013   492.1  1415.9   496.3 1415.85
   502.11417.056     513 1419.51   552.8 1434.71   578.2  1443.7   610.3 1458.15
#Mann= 6 ,-1,0
       0     .05       0      70     .06       0  169.52     .05       0
  474.06      .1       0  486.92    .045       0   502.1      .1       0
Bank Sta=486.92,502.1
XS Rating Curve= 0 ,0
Exp/Cntr=0.3,0.1

Type RM Length L Ch R = 1 ,17672   ,368.8,368.7,364
XS GIS Cut Line= 4
2184698.30424181743173.402050569 2184735.8787919742969.465461918
2184636.28648431742647.4838238812184592.79880875742533.497910863
#Sta/Elev= 30
       0 1437.67    36.8 1429.45    61.2 1425.88    89.7 1422.89   138.5 1422.97
   154.8 1422.33   167.5 1421.08   179.2 1421.59   195.5 1421.42   241.2 1419.23
   258.5 1417.67   299.8 1416.97   433.8 1417.13   450.4 1417.49   463.6 1419.37
   471.4  1419.9   482.4 1417.94   495.2 1417.47   500.51416.574   504.9 1415.74
   509.1 1415.62  514.811416.576   521.7 1418.59     564 1423.88   592.8 1430.96
   611.1 1437.23   619.6 1439.62   641.1 1443.44   649.6 1447.27   666.4 1457.35
#Mann= 6 ,-1,0
       0     .05       0     110     .06       0  207.37     .05       0
  397.37      .1       0   500.5    .045       0  514.81      .1       0
Bank Sta=500.5,514.81
XS Rating Curve= 0 ,0
Exp/Cntr=0.3,0.1