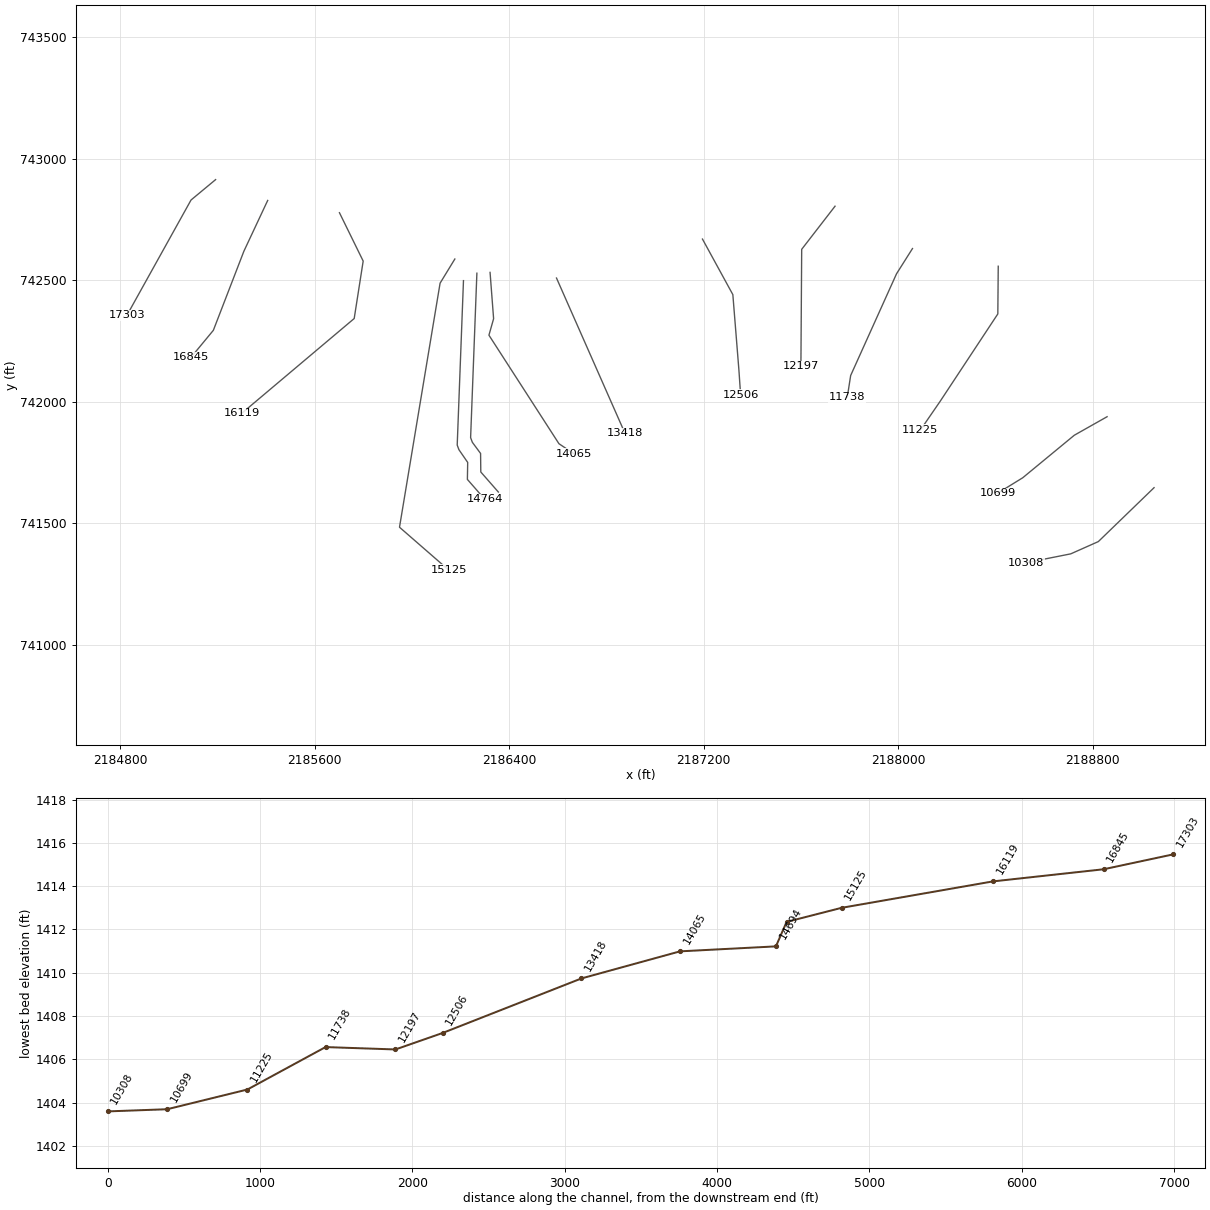
HEC-RAS study TURKEYRN.prj: TURKEYRN

--- TURKEYRN.g01 (geometry) --- (continued)

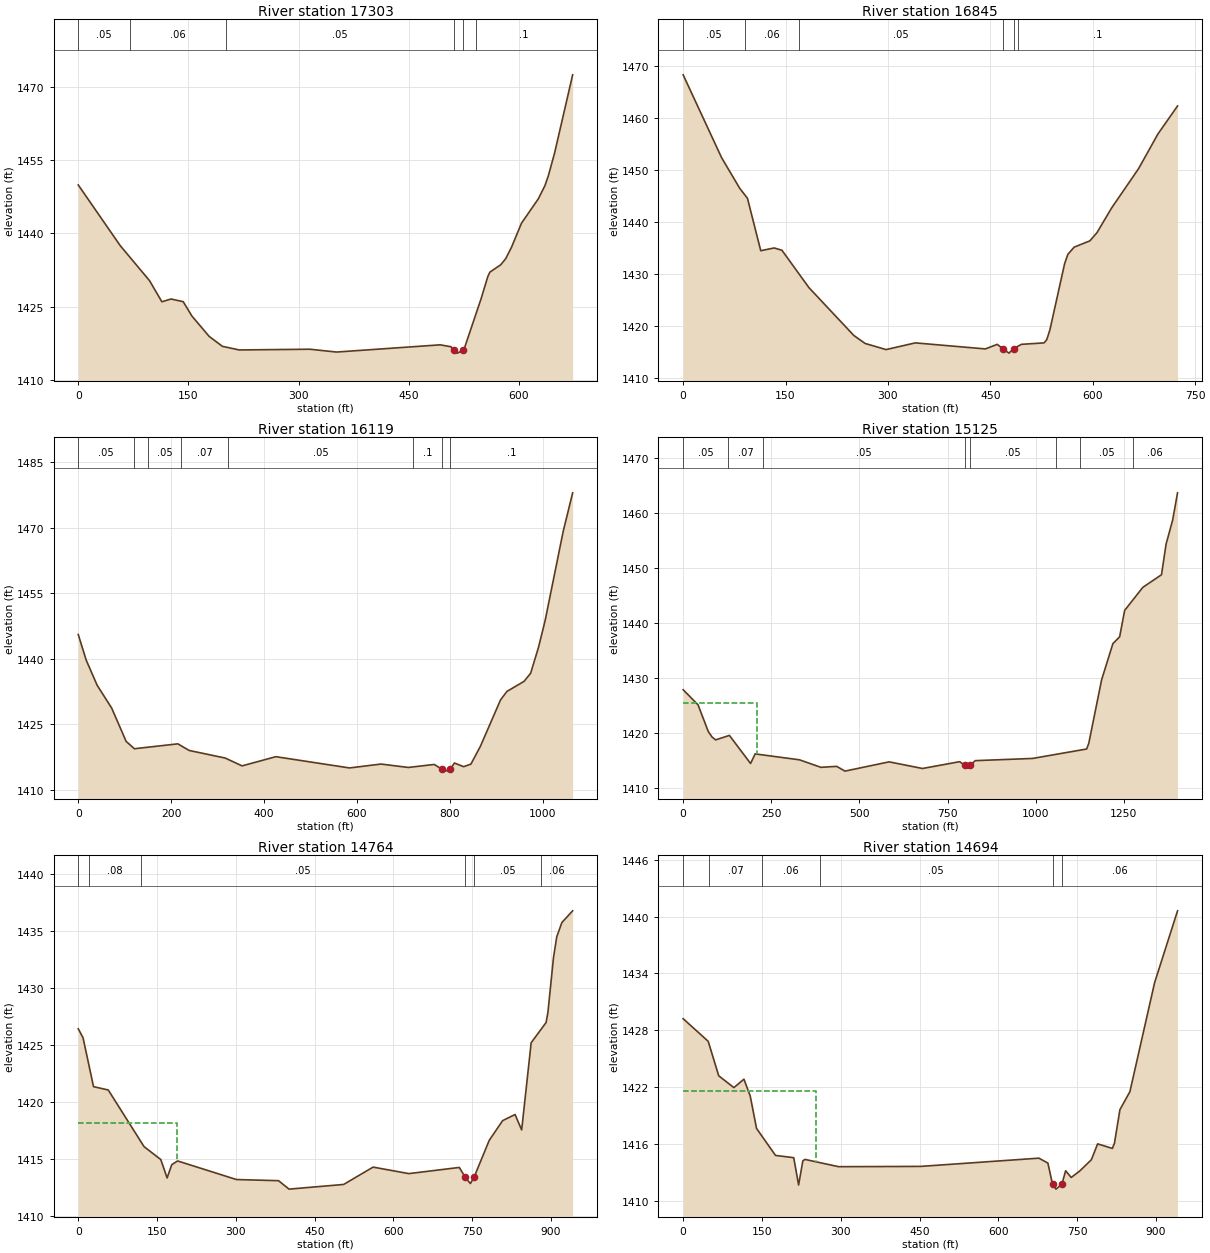
Type RM Length L Ch R = 1 ,17303   ,453.4,458.2,457.4
XS GIS Cut Line= 3
2185192.19265219742913.9302249582185091.12944409742830.034255758
 2184827.7940681742356.232706858
#Sta/Elev= 30
       0 1449.93    57.2 1437.49    97.1 1430.32   113.9 1425.99   126.4 1426.56
     143 1426.01   154.7 1423.09   178.3  1418.9   196.4 1416.86   219.3 1416.12
   315.4 1416.27   351.8 1415.69     493 1417.17   507.6 1416.78  511.471416.101
   516.7 1415.47   524.11416.108   525.9 1416.45   548.8 1426.67   557.9 1431.19
   560.7 1432.07   575.4 1433.57   582.1  1434.8     590 1437.13   603.7  1442.1
   626.6 1447.08   635.7 1449.82   640.3 1451.82   648.9 1456.54   673.4  1472.5
#Mann= 6 ,-1,0
       0     .05       0      70     .06       0  201.35     .05       0
  511.47    .045       0   524.1     .05       0  541.35      .1       0
Bank Sta=511.47,524.1
XS Rating Curve= 0 ,0
Exp/Cntr=0.3,0.1

Type RM Length L Ch R = 1 ,16845   ,722.8,726.2,710.6
XS GIS Cut Line= 4
2185406.42165968742828.1756096652185308.49563434742619.258731019
2185182.88104639742293.7267593692185090.73737861742182.289187361
#Sta/Elev= 30
       0 1468.31    56.3 1452.38    82.8  1446.5    94.2 1444.57   113.7 1434.48
   133.3 1435.01   144.7 1434.57   184.4 1427.36   250.1 1418.17   266.6 1416.64
   297.3 1415.46   340.1 1416.75   442.7 1415.59   460.2 1416.47  468.28 1415.62
   477.3 1414.78     4841415.625   495.5 1416.47   528.8 1416.75   532.7 1417.37
   537.4  1419.3   558.8 1431.96   563.6 1433.78   572.9 1435.17   595.9 1436.38
   606.3 1437.96   627.8 1442.72   667.2 1450.26   695.6 1456.94   724.3 1462.32
#Mann= 6 ,-1,0
       0     .05       0      90     .06       0     170     .05       0
  468.28    .045       0     484     .05       0  490.73      .1       0
Bank Sta=468.28,484
XS Rating Curve= 0 ,0
Exp/Cntr=0.3,0.1

Type RM Length L Ch R = 1 ,16119   ,976.1,993.3,993.5
XS GIS Cut Line= 4
2185701.62839618742777.7029814562185799.21478783742578.722874047
2185762.27273849 742342.293758252185300.67428723741953.091618942
#Sta/Elev= 30
       0 1445.51    17.2 1439.63    40.7 1433.89    71.9 1428.68   103.1 1421.04
   120.9 1419.35   214.5 1420.47     239 1418.95   316.7 1417.21   352.7 1415.42
   425.6 1417.53     584 1414.95     652 1415.84   710.9 1415.06   766.7 1415.75
     784 1414.61   789.6 1414.22     801 1414.61   810.1 1416.08   829.9 1415.24
   845.6 1415.83     866  1419.9   909.4 1430.54   923.1 1432.48     960 1434.78
   974.2 1436.64   991.2  1442.6  1005.4 1448.71  1044.4 1469.18  1064.7 1477.98
#Mann= 8 ,-1,0
       0     .05       0     120     .06       0     150     .05       0
  221.62     .07       0  321.62     .05       0  720.92      .1       0
     784    .045       0     801      .1       0
Bank Sta=784,801
XS Rating Curve= 0 ,0
Exp/Cntr=0.3,0.1

Type RM Length L Ch R = 1 ,15125   ,346.4,361.1,366.5
XS GIS Cut Line= 4
2186176.24815268742587.1639812012186115.58649841742487.845432663
2185948.61979578741483.5568998332186150.52005348741307.784070338
#Sta/Elev= 30
       0 1427.83    42.2 1425.08    71.3 1420.21      82 1419.21    92.2 1418.69
   131.2 1419.51   191.2 1414.39   204.2 1416.14   329.9 1415.06   390.8 1413.69
   435.4 1413.87   458.9    1413   584.1 1414.69   678.7 1413.48   784.1 1414.72
   799.7 1414.03   812.5 1414.04   828.7 1414.91   990.9 1415.31  1144.2 1417.03
  1150.3 1418.05  1186.8 1429.65  1218.7 1436.22  1237.9 1437.47  1252.1 1442.28
  1303.6 1446.48  1356.6 1448.78  1369.6 1454.36  1388.2 1458.73  1402.1  1463.7
#Mann= 8 ,-1,0
       0     .05       0  126.38     .07       0  226.38     .05       0
   799.7    .045       0   812.5     .05       0 1056.38      .1       0
 1126.38     .05       0 1274.45     .06       0
#XS Ineff= 2 , 0
          209.13 1425.45
Permanent Ineff=
       F       F
Bank Sta=799.7,812.5
XS Rating Curve= 0 ,0
Exp/Cntr=0.3,0.1

Type RM Length L Ch R = 1 ,14764   ,65.4,70.2,71.6
XS GIS Cut Line= 6
2186211.78122808742498.262047401 2186185.9845131741821.534431304
2186193.16604749741802.3836729252186229.11544847741750.264319139
2186227.87679705741680.2975882552186300.13258782741597.743953915
#Sta/Elev= 30
       0  1426.4     9.1 1425.62    29.1 1421.33    57.1 1421.04   125.2 1416.08
   157.2 1414.94   169.2 1413.33     178 1414.49   189.2 1414.82   301.3 1413.19
   381.4 1413.09   401.4 1412.35   505.4 1412.76   561.5 1414.28   629.5 1413.71
   725.7 1414.25  736.831413.392   746.7 1412.84   753.71413.389   782.7 1416.63
   808.1 1418.35   831.8 1418.89   844.4 1417.54   862.5 1425.18   890.9 1426.95
   894.4 1427.84     905 1432.64   911.2 1434.46     921 1435.72   941.5 1436.74
#Mann= 6 ,-1,0
       0     .05       0      20     .08       0     120     .05       0
  736.83    .045       0   753.7     .05       0  881.78     .06       0
#XS Ineff= 2 , 0
          188.17 1418.14
Permanent Ineff=
       F       F
Bank Sta=736.83,753.7
XS Rating Curve= 0 ,0
Exp/Cntr=0.3,0.1

Type RM Length L Ch R = 1 ,14694   ,620.4,629.3,617
XS GIS Cut Line= 6
2186266.92900532742528.8158959492186241.13229034741852.088279852
2186248.31382473741832.9375214722186282.14291358741787.179104051
2186283.02457429741710.8514368032186355.28036505741628.297802463
#Sta/Elev= 30
       0 1429.22    47.7 1426.83    67.7 1423.19    96.6 1421.94   115.7 1422.83
   127.7 1421.05   139.7 1417.63   175.8 1414.78   210.5 1414.54   219.8 1411.66
   227.8  1414.2   231.8 1414.36   295.9 1413.59     452 1413.62   677.2 1414.49
   694.3 1413.97   703.1 1411.73   709.7 1411.22  720.881411.727   728.1 1413.16
   738.7 1412.45   754.8 1413.13     777 1414.32     789    1416     817 1415.52
     821 1416.07   831.4 1419.61   850.4 1421.51   897.4 1433.02   941.1 1440.61
#Mann= 6 ,-1,0
       0     .06       0      50     .07       0     150     .06       0
     260     .05       0   703.1    .045       0  720.88     .06       0
#XS Ineff= 2 , 0
          253.52 1421.56
Permanent Ineff=
       F       F
Bank Sta=703.1,720.88
XS Rating Curve= 0 ,0
Exp/Cntr=0.3,0.1

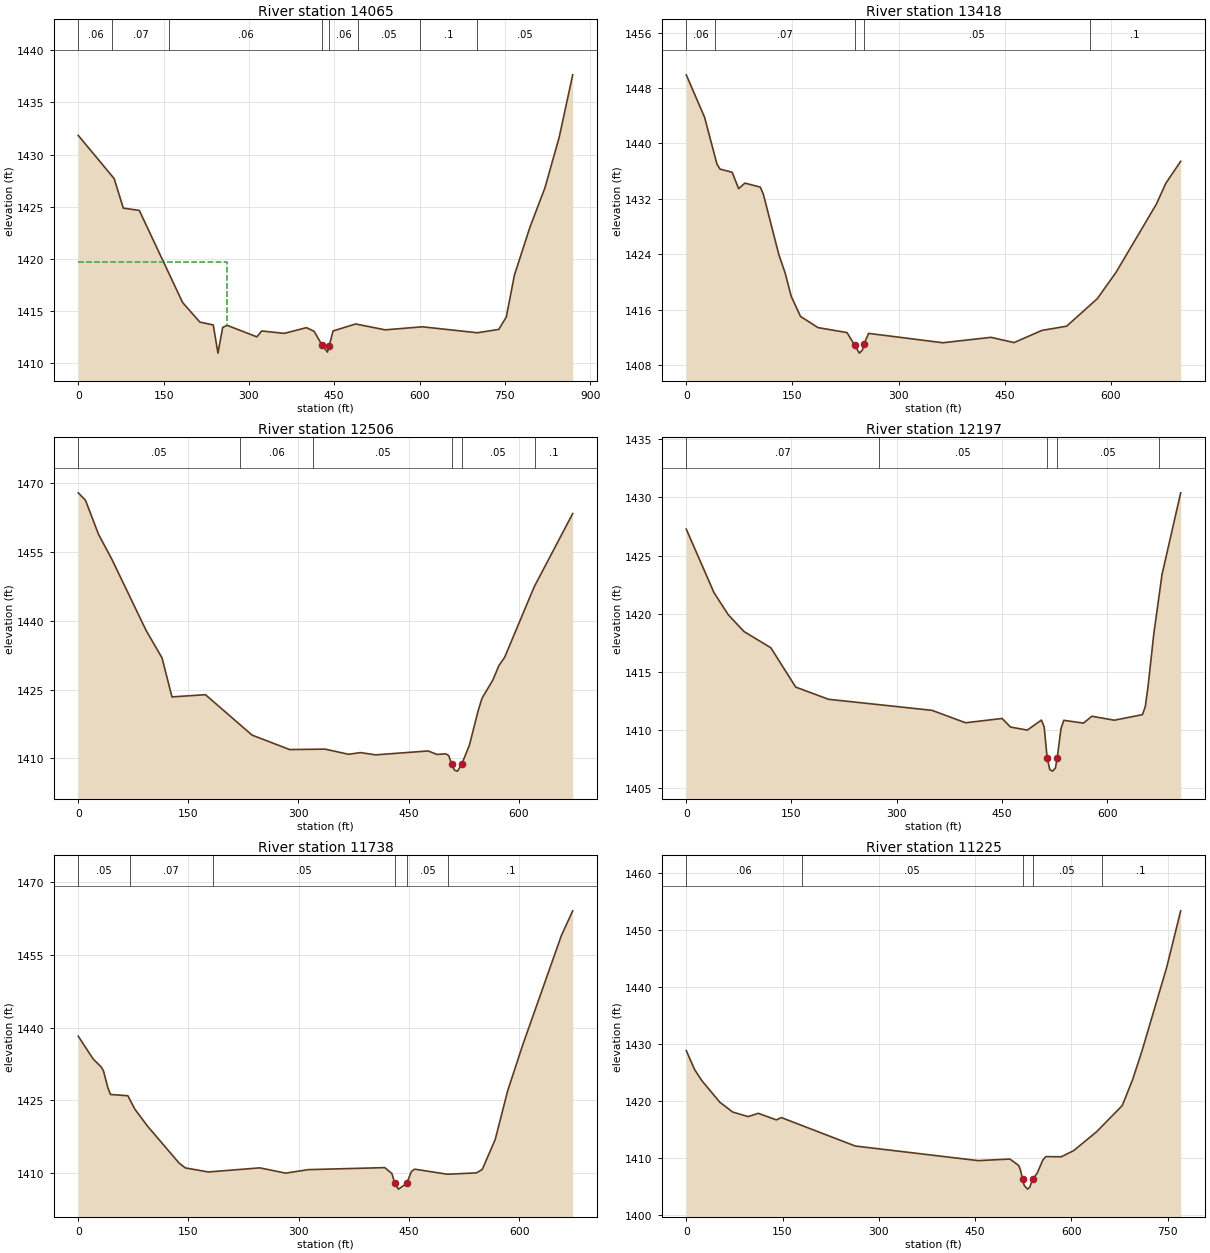
Type RM Length L Ch R = 1 ,14065   ,643,646.8,639.8
XS GIS Cut Line= 5
 2186321.1560037742532.146700241 2186335.7243314742341.610003564
2186316.51581739742273.7711067732186604.50746513741827.185385762
2186667.84092729741784.828503373
#Sta/Elev= 30
       0 1431.83    63.2 1427.69    79.2 1424.87   107.3 1424.65   183.5 1415.83
   213.8 1413.96   237.3 1413.69   245.6 1410.99   253.9 1413.45   261.8 1413.65
   313.9 1412.55   322.5 1413.11   362.3 1412.88   401.2 1413.43   414.6 1413.08
   428.9 1411.73   438.1 1411.09   441.2  1411.7   447.9 1413.11   487.5 1413.78
   539.6 1413.22     605 1413.51   701.6 1412.94   739.2 1413.26   752.5 1414.45
   766.8 1418.47   794.2 1423.07   820.2 1426.78   845.5 1431.66   869.2 1437.63
#Mann= 8 ,-1,0
       0     .06       0      60     .07       0     160     .06       0
   428.9    .045       0   441.2     .06       0   491.6     .05       0
   601.6      .1       0   701.6     .05       0
#XS Ineff= 2 , 0
          261.83 1419.68
Permanent Ineff=
       F       F
Bank Sta=428.9,441.2
XS Rating Curve= 0 ,0
Exp/Cntr=0.3,0.1

Type RM Length L Ch R = 1 ,13418   ,907.6,911.8,902.2
XS GIS Cut Line= 2
2186594.44645833742508.8979170762186876.26902528 741869.82072063
#Sta/Elev= 30
       0 1449.91    25.9 1443.78    43.4 1437.01    47.8  1436.3    64.8 1435.85
      74 1433.48    82.8 1434.28   104.6  1433.7     109 1432.65   130.8 1423.96
   139.6 1421.34   148.3 1417.94   161.4 1415.04   186.2 1413.42     227 1412.71
   237.81410.916   244.5 1409.74   248.9 1410.19   251.2  1411.1   257.6 1412.59
   362.5 1411.24   430.6 1412.02   463.1 1411.26   502.4 1413.02   537.4 1413.63
   580.6 1417.59   607.4 1421.44   664.2 1431.26   677.6 1434.27   698.5 1437.43
#Mann= 5 ,-1,0
       0     .06       0      40     .07       0   237.8    .045       0
   251.2     .05       0     570      .1       0
Bank Sta=237.8,251.2
XS Rating Curve= 0 ,0
Exp/Cntr(USF)=0,0
Exp/Cntr=0.3,0.1

Type RM Length L Ch R = 1 ,12506   ,309.6,309.4,307.4
XS GIS Cut Line= 4
2187194.85461903742669.2660952352187319.81381747742440.734849236
2187344.77493576742129.8891809052187351.72273215742028.752130741
#Sta/Elev= 30
       0 1467.92     9.9 1466.28    27.6 1458.87    45.7 1453.45    92.4 1437.92
   114.1 1431.93   127.7 1423.41   173.3 1423.89   236.8 1415.08   288.1 1411.92
   336.3 1412.02   368.4 1410.89   384.4 1411.26   405.3 1410.77   476.7 1411.62
   488.8 1410.86   500.8 1410.99   504.8 1410.61   508.8 1408.71   512.8 1407.41
   516.8 1407.22  522.371408.704   532.9 1412.84   544.9 1420.41   550.1  1423.1
     565 1427.12     573 1430.19     581 1432.05   621.1 1447.37   673.7 1463.39
#Mann= 6 ,-1,0
       0     .05       0     220     .06       0  320.46     .05       0
   508.8    .045       0  522.37     .05       0  622.31      .1       0
Bank Sta=508.8,522.37
XS Rating Curve= 0 ,0
Exp/Cntr=0.3,0.1

Type RM Length L Ch R = 1 ,12197   ,458.4,458.6,449.2
XS GIS Cut Line= 3
2187740.18523016742804.5725159222187602.99777713742627.106305325
2187599.76608666742146.661654478
#Sta/Elev= 30
       0 1427.28    39.5 1421.82    59.9 1419.91    82.3 1418.47   120.6 1417.07
     156 1413.69   202.8 1412.64   350.2 1411.69   398.2 1410.62   450.2 1410.99
   462.2 1410.25   486.2 1409.99   506.2 1410.85   510.2 1410.26  514.451407.603
   518.2 1406.59   522.2 1406.46   526.2 1406.72   528.81407.614   534.2 1410.13
   538.2 1410.83   566.2 1410.59   578.2 1411.18   610.2 1410.84   650.3 1411.32
   654.3    1412   658.2 1413.71   666.4 1418.23   678.2 1423.38   704.8  1430.4
#Mann= 5 ,-1,0
       0     .07       0  274.31     .05       0  514.45    .045       0
   528.8     .05       0  674.31      .1       0
Bank Sta=514.45,528.8
XS Rating Curve= 0 ,0
Exp/Cntr=0.3,0.1

Type RM Length L Ch R = 1 ,11738   ,510.2,513.1,506.2
XS GIS Cut Line= 4
2188058.73431746742630.2738888962187993.02557145742526.287214319
2187804.43981684 742107.881368762187790.46751589742018.026730181
#Sta/Elev= 30
       0  1438.2    20.2 1433.51    31.6 1431.77    34.4 1430.99    40.3 1427.55
    43.9 1426.15    67.5 1425.89      77 1423.12    94.6 1419.54   137.4 1411.93
   145.7 1410.96   176.9 1410.12   247.1 1410.97   282.2 1409.88   312.9  1410.6
   417.1 1411.02   426.9 1409.78   430.61407.857   435.7 1406.57   447.1 1407.76
   453.3 1410.19   457.7  1410.7   502.5 1409.65   541.9 1409.93   549.8 1410.64
   567.4 1416.81   584.5 1426.96   604.9  1436.4   657.5 1459.02   672.9 1464.14
#Mann= 6 ,-1,0
       0     .05       0      70     .07       0  183.01     .05       0
   430.6    .045       0   447.1     .05       0  503.01      .1       0
Bank Sta=430.6,447.1
XS Rating Curve= 0 ,0
Exp/Cntr=0.3,0.1

Type RM Length L Ch R = 1 ,11225   ,525.7,526.4,516.8
XS GIS Cut Line= 4
2188411.51026242742557.4911692192188409.78355279742361.232256472
2188172.57280109742001.683834462 2188091.2965402 741883.50010574
#Sta/Elev= 30
       0 1428.91    13.1 1425.58    24.3 1423.64    52.3 1419.86    72.3 1418.14
    96.3 1417.34   112.3 1417.91   140.3 1416.76   148.3 1417.16   263.4 1412.17
   455.1 1409.61   504.3 1409.89     518 1408.76   520.8 1407.96   524.11406.344
   526.6 1405.26   531.8 1404.61   535.3 1404.97   539.61406.303   546.8 1407.41
   555.7 1409.74   560.5 1410.32   584.2 1410.28   603.7 1411.37   639.2 1414.66
   679.4 1419.28   695.6 1423.86   710.2  1428.9   748.5 1443.49   770.4 1453.44
#Mann= 5 ,-1,0
       0     .06       0     180     .05       0   524.1    .045       0
   539.6     .05       0  647.01      .1       0
Bank Sta=524.1,539.6
XS Rating Curve= 0 ,0
Exp/Cntr=0.3,0.1

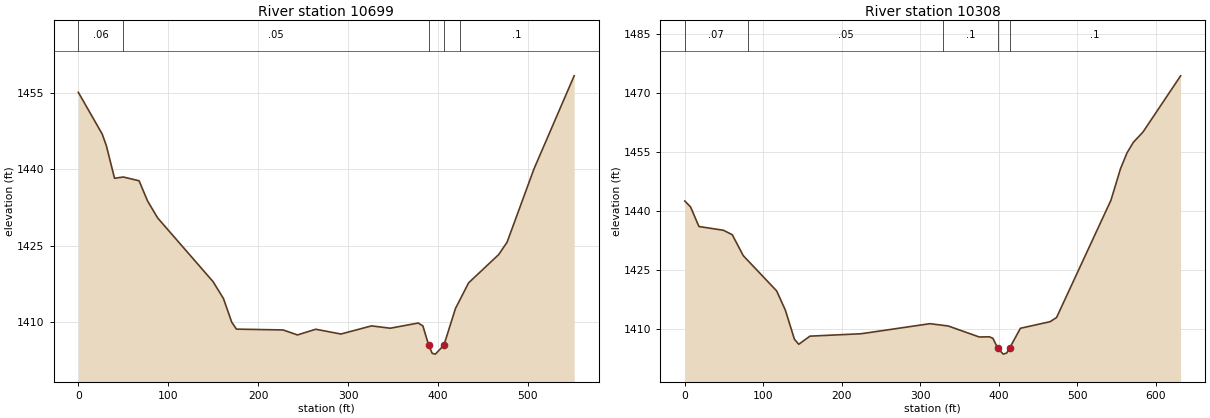
Type RM Length L Ch R = 1 ,10699   ,393.7,390.7,387
XS GIS Cut Line= 4
2188859.22779384741938.3008612652188724.50934295741862.162204217
2188512.34544987741687.1714190042188408.68367002741623.244618479
#Sta/Elev= 30
       0 1455.14    26.5 1446.96    31.1  1444.7    40.3 1438.25      50  1438.5
    67.6 1437.76      77  1433.8    88.2 1430.47   149.8 1417.96   161.4 1414.64
   170.7 1409.96   175.9 1408.61   227.8 1408.45   243.8 1407.47   264.1 1408.59
   292.1 1407.65   326.2 1409.25     347 1408.79   378.1 1409.81   383.3 1409.25
   389.8 1405.45   393.7 1403.85   397.2  1403.7  406.731405.473   419.6 1412.68
   434.2 1417.71   467.6 1423.25     477  1425.7   506.9 1440.09   551.6 1458.38
#Mann= 5 ,-1,0
       0     .06       0      50     .05       0   389.8    .045       0
  406.73     .05       0  424.75      .1       0
Bank Sta=389.8,406.73
XS Rating Curve= 0 ,0
Exp/Cntr=0.3,0.1

Type RM Length L Ch R = 1 ,10308   ,270.6,275.4,279.5
XS GIS Cut Line= 4
2189052.45549145741646.2921021082188823.19619053741424.420819737
2188709.68551941741373.959776711  2188525.150745741337.214190529
#Sta/Elev= 30
       0 1442.52     7.4    1441      18 1436.04    49.1 1435.09    60.4 1433.96
    74.5 1428.62     117 1419.66   128.1 1414.76   139.6 1407.39   145.1  1406.1
   159.4 1408.17   224.5 1408.78   312.2 1411.34   335.5 1410.75   374.9 1407.96
     388    1408   392.4 1407.61   398.51405.099   405.5  1403.6   409.9 1403.88
   413.51405.092   427.4 1410.17   465.2 1411.85   473.4  1412.9   542.7 1442.73
   554.9 1450.76   563.1 1454.74   571.2 1457.44   583.5 1460.06   631.4 1474.34
#Mann= 5 ,-1,0
       0     .07       0      80     .05       0  329.04      .1       0
   398.5    .045       0   413.5      .1       0
Bank Sta=398.5,413.5
XS Rating Curve= 0 ,0
Exp/Cntr=0.3,0.1