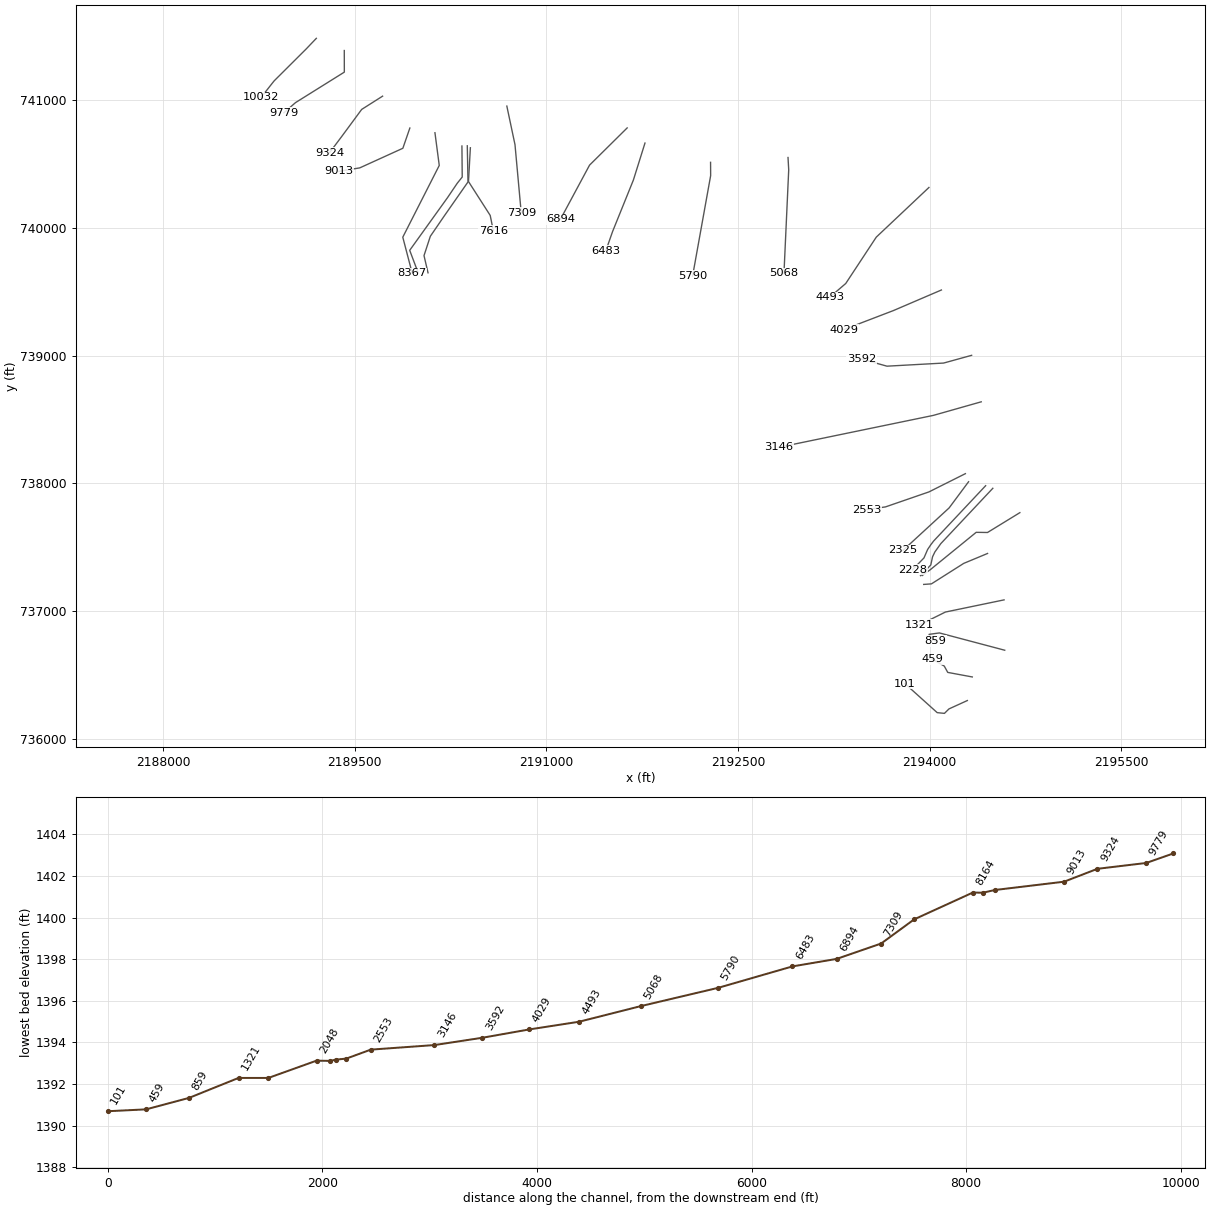
HEC-RAS study TURKEYRN.prj: TURKEYRN

--- TURKEYRN.g01 (geometry) --- (continued)

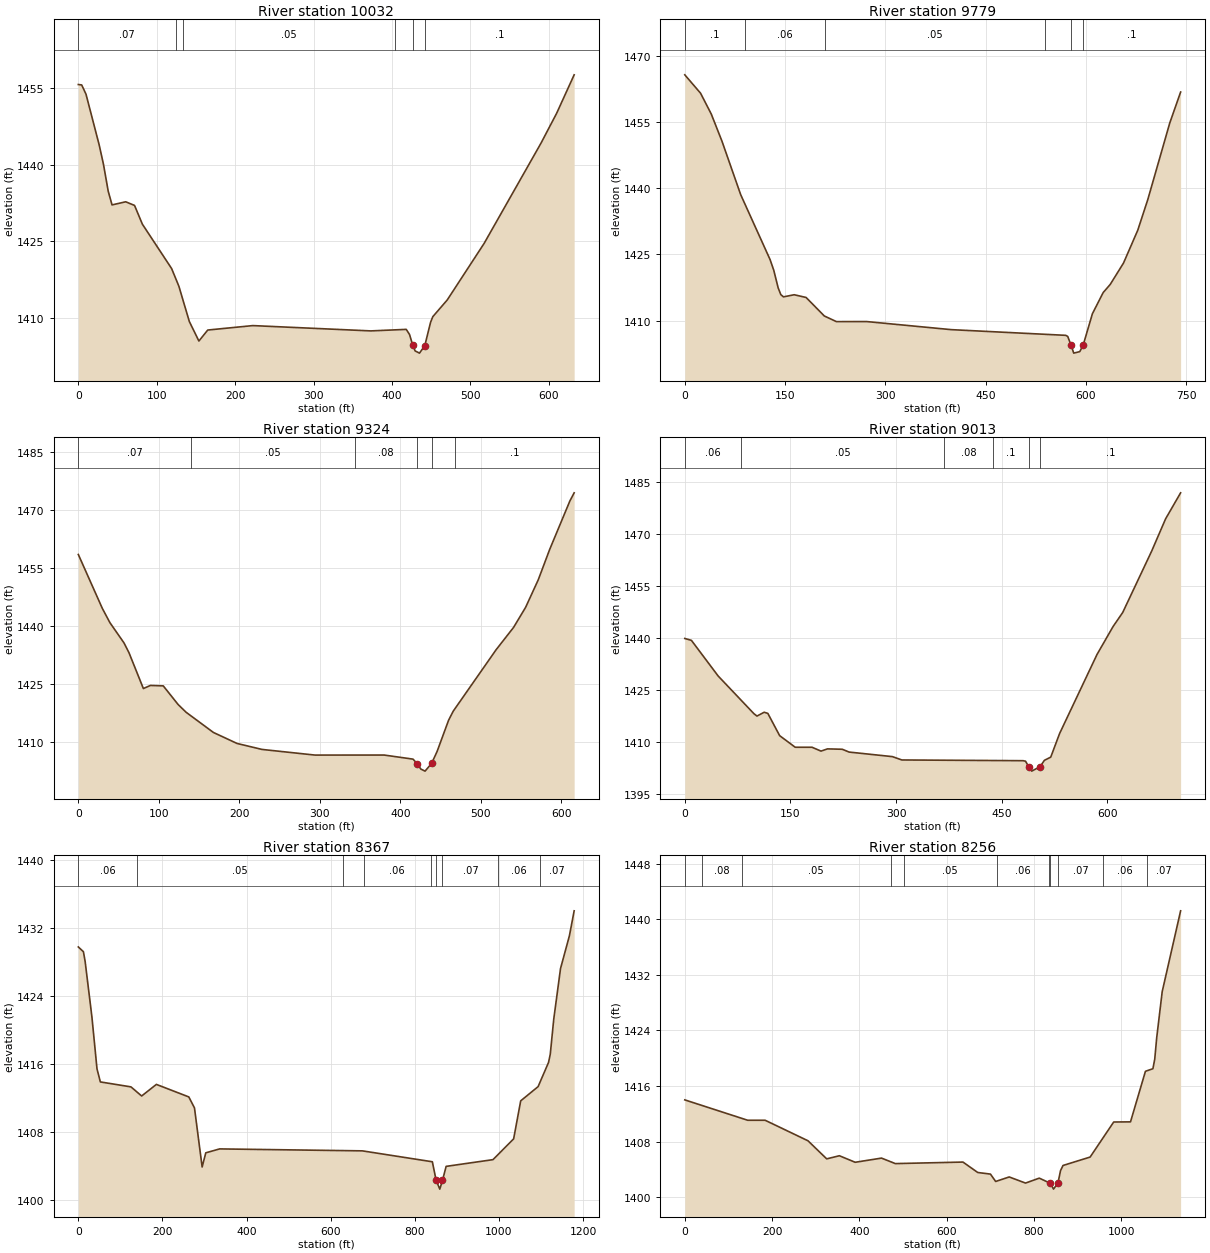
Type RM Length L Ch R = 1 ,10032   ,256.2,254,249.6
XS GIS Cut Line= 4
2189198.50750171741484.2598656582189119.63697803741401.775023954
 2188867.7974906741150.8297986792188766.96524329741022.991653163
#Sta/Elev= 30
       0 1455.67     4.3 1455.59     9.8 1453.77    26.5 1443.91    32.1 1440.03
    38.1  1434.8      43  1432.1    60.4 1432.71    71.7    1432    81.7 1428.33
     119 1419.64   128.3 1416.16   141.6 1409.27   153.8 1405.45   165.1  1407.6
   222.6 1408.47   373.1 1407.43   418.3 1407.73   422.5 1406.73   426.7 1404.58
   429.6 1403.52   435.2 1403.08  441.97 1404.54   449.3  1409.1   452.2 1410.22
   470.6 1413.49   517.6 1424.55   590.2 1444.19   610.1 1450.02   632.5 1457.57
#Mann= 6 ,-1,0
       0     .07       0  124.12     .06       0  134.12     .05       0
  404.12      .1       0   426.7    .045       0  441.97      .1       0
Bank Sta=426.7,441.97
XS Rating Curve= 0 ,0
Exp/Cntr=0.3,0.1

Type RM Length L Ch R = 1 ,9779    ,448.6,454.1,459.1
XS GIS Cut Line= 4
2189417.34395274741388.7838275752189417.71930724741219.732848369
2189035.07847844740980.7143212812188943.96142859740900.804807162
#Sta/Elev= 30
       0 1465.68    23.6 1461.51    39.6 1456.79    55.6 1450.64    83.6 1438.52
   127.6 1423.79   133.1 1421.36   139.6 1417.41   143.6 1415.87   147.6 1415.37
   163.6 1415.85   181.4 1415.23   208.6 1411.04   226.7 1409.76     272 1409.77
   398.5 1407.94   569.7 1406.65   572.6  1406.4   577.61404.391   581.6 1402.62
   590.6 1402.96  595.631404.412   609.5 1411.55   625.6 1416.34   636.1 1418.18
     656 1423.03   677.3 1430.46   692.3 1437.41   725.2 1454.78   741.4 1461.78
#Mann= 6 ,-1,0
       0      .1       0      90     .06       0  209.05     .05       0
  539.05     .08       0   577.6    .045       0  595.63      .1       0
Bank Sta=577.6,595.63
XS Rating Curve= 0 ,0
Exp/Cntr=0.3,0.1

Type RM Length L Ch R = 1 ,9324    ,317,311.4,302.8
XS GIS Cut Line= 4
2189717.29550922741031.5572289442189553.55250922740927.759590794
2189396.49096824740714.8088348682189301.96528623740588.952563446
#Sta/Elev= 30
       0 1458.37    29.7 1444.48    39.2 1440.75    56.7 1435.51    62.9 1432.98
    80.8  1423.7    89.5  1424.5   105.5 1424.39     124 1419.56   133.9 1417.56
   167.8 1412.34   197.1  1409.5   228.2 1407.95     294 1406.49   379.8  1406.5
   415.8 1405.44   420.7  1404.3   425.5 1402.87   430.7 1402.34   438.8 1404.33
   445.6  1407.4   459.9 1415.49   465.7 1417.85   518.9 1433.72   540.6  1439.5
   555.6  1444.7   571.3 1451.82   585.6 1459.73   610.6 1472.22   615.9 1474.32
#Mann= 6 ,-1,0
       0     .07       0     140     .05       0  343.87     .08       0
   420.7    .045       0   438.8     .08       0  468.48      .1       0
Bank Sta=420.7,438.8
XS Rating Curve= 0 ,0
Exp/Cntr=0.3,0.1

Type RM Length L Ch R = 1 ,9013    ,635.9,646.4,652.9
XS GIS Cut Line= 4
2189930.67467193740782.0173943042189875.93035684740623.526072592
2189538.36793421740470.0038197372189375.16035463740442.920498025
#Sta/Elev= 30
       0 1439.88     9.4 1439.34    47.4 1429.08    98.2 1418.23   102.5 1417.56
   112.7 1418.66   117.9 1418.33   134.7 1411.92   156.8 1408.59   180.6 1408.59
   193.4 1407.48   202.6 1408.12   223.6 1408.01   233.3  1407.2   294.8 1405.89
   308.2 1404.93   480.4 1404.72   483.8 1404.58   488.2 1403.02   492.6 1401.72
   504.5 1403.02   510.6 1404.83   519.6 1405.75   532.1 1412.51   585.3 1435.28
   608.2 1443.35   621.8 1447.36   662.9 1465.02   682.7 1474.31     704 1481.78
#Mann= 6 ,-1,0
       0     .06       0      80     .05       0  367.68     .08       0
  437.68      .1       0   488.2    .045       0   504.5      .1       0
Bank Sta=488.2,504.5
XS Rating Curve= 0 ,0
Exp/Cntr=0.3,0.1

Type RM Length L Ch R = 1 ,8367    ,113.1,110.7,108.9
XS GIS Cut Line= 4
2190127.14070185740745.174469337 2190160.8878403740489.149226603
2189875.33056309739927.4115467382189948.82246009739646.253246054
#Sta/Elev= 30
       0 1429.74    12.1 1429.18    16.1 1428.07    32.3 1421.53    44.4 1415.43
    52.4  1413.9   125.1 1413.32   150.6 1412.25   185.6 1413.61   262.7 1412.14
   276.2 1410.85   294.4 1403.92   303.1 1405.58   336.1 1406.04   675.5 1405.81
   841.8 1404.53   850.8 1402.36   859.5 1401.32  865.841402.334   874.6 1403.99
     986 1404.78  1035.1 1407.22  1051.9 1411.68  1093.3 1413.35  1118.1 1416.19
  1122.2 1417.15  1130.5 1421.28  1146.6 1427.21  1167.7 1431.05    1179 1433.98
#Mann= 9 ,-1,0
       0     .06       0     140     .05       0  628.24     .07       0
  678.24     .06       0  838.24     .07       0   850.8    .045       0
  865.84     .07       0  998.39     .06       0 1098.39     .07       0
Bank Sta=850.8,865.84
XS Rating Curve= 0 ,0
Exp/Cntr=0.3,0.1

Type RM Length L Ch R = 1 ,8256    ,87.9,92.1,95.8
XS GIS Cut Line= 6
2190338.42673326740641.2567430512190340.68328278740398.305581982
2190301.90299706740349.8302248352190225.41965578740236.721058156
2189929.46430607739824.4614739782189995.31684431739649.719457318
#Sta/Elev= 30
       0 1414.02   144.1 1411.09   184.1 1411.09   282.2 1408.14   325.1 1405.54
   354.1 1405.99   390.3 1405.05   450.6 1405.65   482.3 1404.86   637.2 1405.08
   671.1 1403.58   700.2 1403.35   712.1 1402.29   743.2 1402.94   780.5 1402.06
     812 1402.77   837.7 1402.02   844.6 1401.19  854.831402.076   860.7 1403.85
   866.4 1404.59   928.5  1405.8   982.5 1410.84    1021 1410.86  1055.2 1418.13
  1072.3  1418.5  1076.5 1419.86    1081 1422.95  1093.6 1429.58  1135.8  1441.2
#Mann= 11 ,-1,0
       0     .05       0      40     .08       0     130     .05       0
  471.58     .08       0  501.58     .05       0  714.64     .06       0
  834.64     .07       0   837.7    .045       0  854.83     .07       0
  959.08     .06       0 1059.08     .07       0
Bank Sta=837.7,854.83
XS Rating Curve= 0 ,0
Exp/Cntr=0.3,0.1

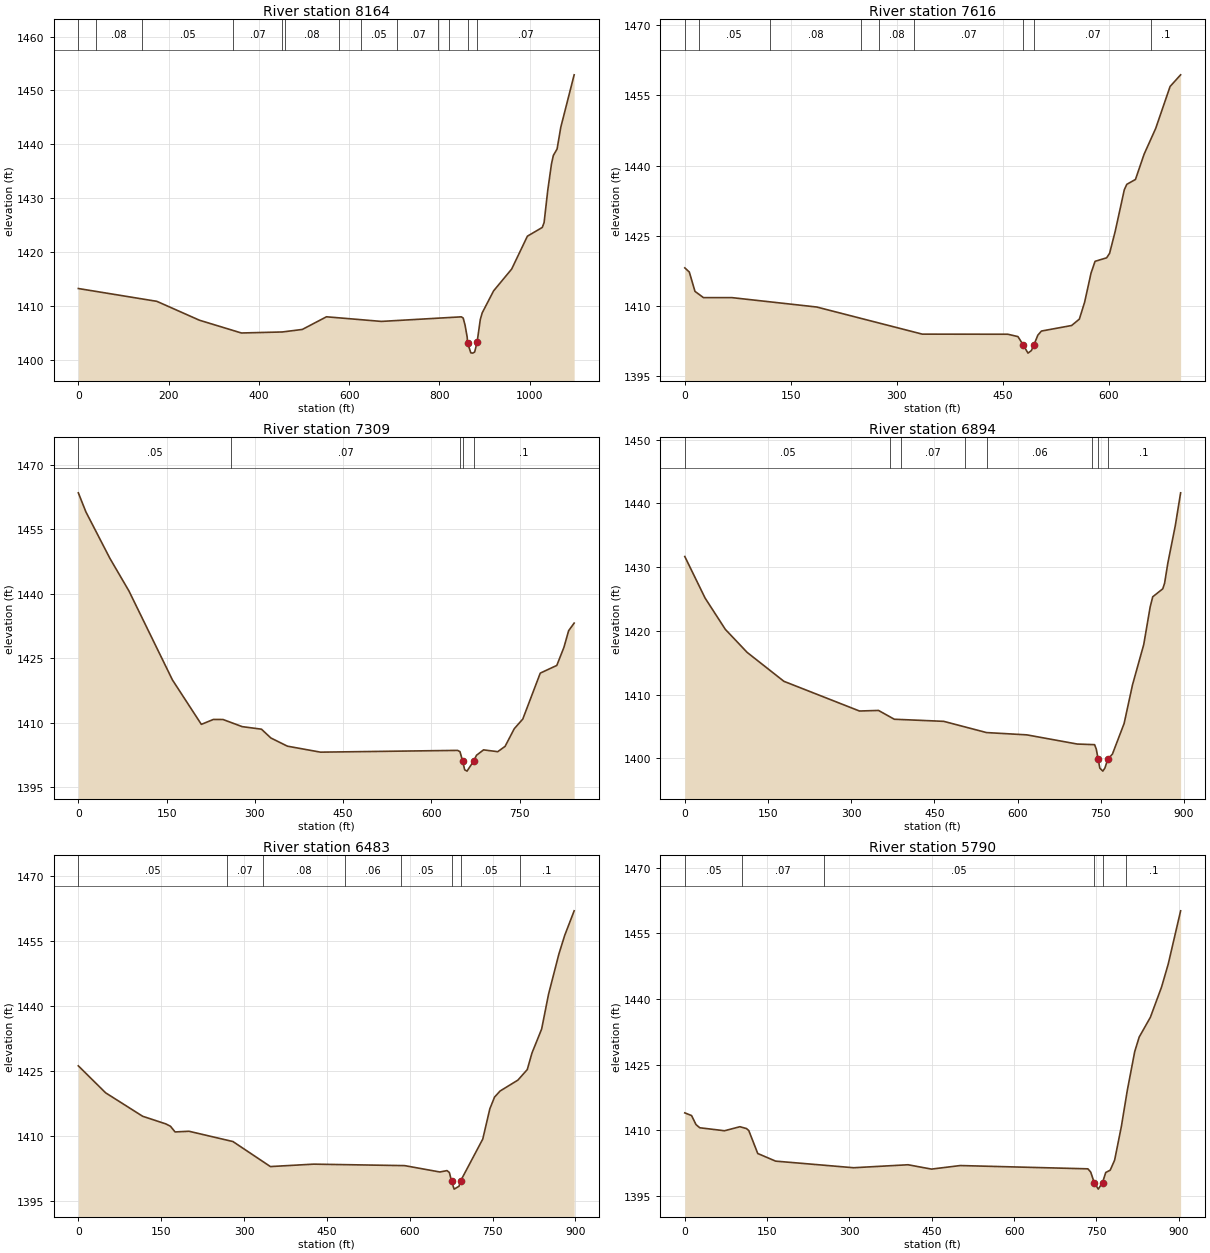
Type RM Length L Ch R = 1 ,8164    ,533.8,547.4,560.6
XS GIS Cut Line= 6
2190380.38491193 740643.018856372190385.96890571740359.941536842
2190195.31113682740086.7014420942190090.99956771739934.364507212
2190041.52322791  739783.06243762190072.93393637739648.360198318
#Sta/Elev= 30
       0  1413.2   173.9 1410.82   268.4 1407.31   361.3 1404.94   452.1 1405.13
   496.3  1405.6   549.8 1407.95   671.4 1407.09   848.5 1407.94   852.7 1407.71
   856.9 1406.36   861.5 1404.17  862.26 1403.17   869.5 1401.26   873.7  1401.2
     878  1401.4   883.4 1403.18   890.6 1407.46   894.8 1408.68     920 1412.76
   960.1 1416.82   994.9 1422.92  1027.8 1424.54  1031.9 1425.44  1040.1  1431.5
  1048.3 1436.36  1052.4 1437.92  1060.7 1439.12  1068.9 1443.16  1098.5 1452.89
#Mann= 13 ,-1,0
       0     .05       0      40     .08       0     140     .05       0
  343.13     .07       0   452.1     .05       0  458.09     .08       0
  578.09     .07       0  626.33     .05       0  706.33     .07       0
  796.33     .06       0  820.96     .07       0  862.26    .045       0
   883.4     .07       0
Bank Sta=862.26,883.4
XS Rating Curve= 0 ,0
Exp/Cntr=0.3,0.1

Type RM Length L Ch R = 1 ,7616    ,313,307.4,299.8
XS GIS Cut Line= 4
2190404.52676261740627.5581861452190389.74143502740363.112279897
2190559.78156135740097.9207793482190584.05751645739978.513665597
#Sta/Elev= 30
       0 1418.14     6.4 1417.25    14.4 1413.12    26.4 1411.78    66.5 1411.78
   186.7 1409.77   336.1 1403.97   457.2 1403.95   471.5 1403.44  478.681401.723
   485.7 1399.91   490.5 1400.46   494.3 1401.75   499.6 1403.74   504.7 1404.63
   547.5 1405.82   558.4 1407.19   565.8 1410.78   574.9 1417.01   580.6 1419.54
     597 1420.29   601.2 1421.26   609.2 1426.01     622 1434.84   625.5    1436
   637.8 1437.05     650 1442.44   666.4 1447.95   686.8 1456.93   701.7 1459.42
#Mann= 9 ,-1,0
       0     .07       0      20     .05       0     120     .08       0
     250     .05       0  274.86     .08       0  324.86     .07       0
  478.68    .045       0   494.3     .07       0  659.88      .1       0
Bank Sta=478.68,494.3
XS Rating Curve= 0 ,0
Exp/Cntr=0.3,0.1

Type RM Length L Ch R = 1 ,7309    ,420.7,414.8,403.8
XS GIS Cut Line= 3
2190690.01224084740953.7584965992190753.87986224740651.616892062
2190802.47457368740119.814197814
#Sta/Elev= 30
       0 1463.44    12.9    1459    53.7  1448.2    86.1 1440.61     160 1419.94
   209.1 1409.62   229.5 1410.76   245.9 1410.75   278.6 1409.09   311.3  1408.5
   327.3 1406.45   355.4 1404.55   411.7 1403.16   644.6 1403.57   648.7 1403.28
   653.21401.119   656.7 1399.06   660.7 1398.75  672.081401.105   676.8 1402.44
   688.8 1403.69   712.9 1403.27   725.4 1404.51     741 1408.61   755.5 1410.86
   785.2 1421.53   813.3 1423.32   825.4 1427.52   833.4 1431.39   842.8 1433.16
#Mann= 5 ,-1,0
       0     .05       0     260     .07       0  648.82      .1       0
   653.2    .045       0  672.08      .1       0
Bank Sta=653.2,672.08
XS Rating Curve= 0 ,0
Exp/Cntr=0.3,0.1

Type RM Length L Ch R = 1 ,6894    ,409.9,411.7,412.5
XS GIS Cut Line= 3
2191632.09927358740782.9003756922191337.50925673 740491.38090989
 2191110.4965933740068.829876528
#Sta/Elev= 30
       0 1431.68    36.6 1425.16    73.1 1420.25   112.4 1416.64   178.7  1412.1
     315 1407.44   349.3 1407.53   377.8 1406.15   466.9 1405.82     544 1404.06
   616.7  1403.7   707.6 1402.26     739 1402.16     742 1401.46   745.31399.934
   748.4 1398.48   753.8 1398.01   757.5 1398.48  762.811399.891   771.1 1400.68
   792.2 1405.48   807.4 1411.57   827.6 1417.87   839.2 1423.78   843.8 1425.36
   861.9 1426.61   865.2 1427.49     871 1430.62   884.6 1436.57   894.1 1441.67
#Mann= 8 ,-1,0
       0     .05       0     370     .06       0     390     .07       0
  504.45     .08       0  544.45     .06       0  734.45      .1       0
   745.3    .045       0  762.81      .1       0
Bank Sta=745.3,762.81
XS Rating Curve= 0 ,0
Exp/Cntr=0.3,0.1

Type RM Length L Ch R = 1 ,6483    ,689.6,692.3,694.7
XS GIS Cut Line= 4
2191771.56032804740664.3427027592191680.74570567740374.661253813
2191517.45020886739970.4162570782191465.18487812739821.091446031
#Sta/Elev= 30
       0 1426.13    49.4  1419.9   116.5 1414.48   158.4 1412.72   166.8 1412.18
   175.2 1410.86   200.3 1411.02     280 1408.64   347.8 1402.86     426 1403.42
   590.9 1403.08   654.6 1401.61   667.6 1401.93   671.9 1401.48  675.781399.466
   680.5 1397.65   689.3 1398.31     6921399.498   732.3 1409.21   745.1 1416.19
   753.6  1418.9   763.5  1420.3     796 1422.84   812.9 1425.27   821.4 1429.09
   838.9 1434.62   851.4 1442.66   870.2 1451.98   880.7 1456.27   897.8 1461.94
#Mann= 8 ,-1,0
       0     .05       0     270     .07       0  333.58     .08       0
  483.58     .06       0  583.58     .05       0  675.78    .045       0
     692     .05       0  799.56      .1       0
Bank Sta=675.78,692
XS Rating Curve= 0 ,0
Exp/Cntr=0.3,0.1

Type RM Length L Ch R = 1 ,5790    ,720,722.1,723.3
XS GIS Cut Line= 3
2192285.08663631740513.5767027592192285.76808428740409.541957543
2192144.25186126739622.933531283
#Sta/Elev= 30
       0 1414.02    12.4  1413.4    20.4 1411.35    27.3 1410.62    72.4 1409.94
   100.4 1410.86   112.4 1410.44   116.6 1409.98   132.9 1404.75   165.4 1403.01
   307.6  1401.5   406.7 1402.18   449.4 1401.19   501.8    1402   734.4 1401.25
   739.5 1400.51   745.91398.121   753.3 1396.62  761.02 1398.12   766.9 1400.42
     775 1400.94   783.1 1403.25   795.3 1410.88   806.2 1419.18   819.7 1428.01
   827.8 1431.31   848.2 1435.83   868.5 1442.71   880.7 1447.96   903.3 1460.12
#Mann= 6 ,-1,0
       0     .05       0  104.04     .07       0  254.04     .05       0
   745.9    .045       0  761.02     .05       0  804.04      .1       0
Bank Sta=745.9,761.02
XS Rating Curve= 0 ,0
Exp/Cntr=0.3,0.1

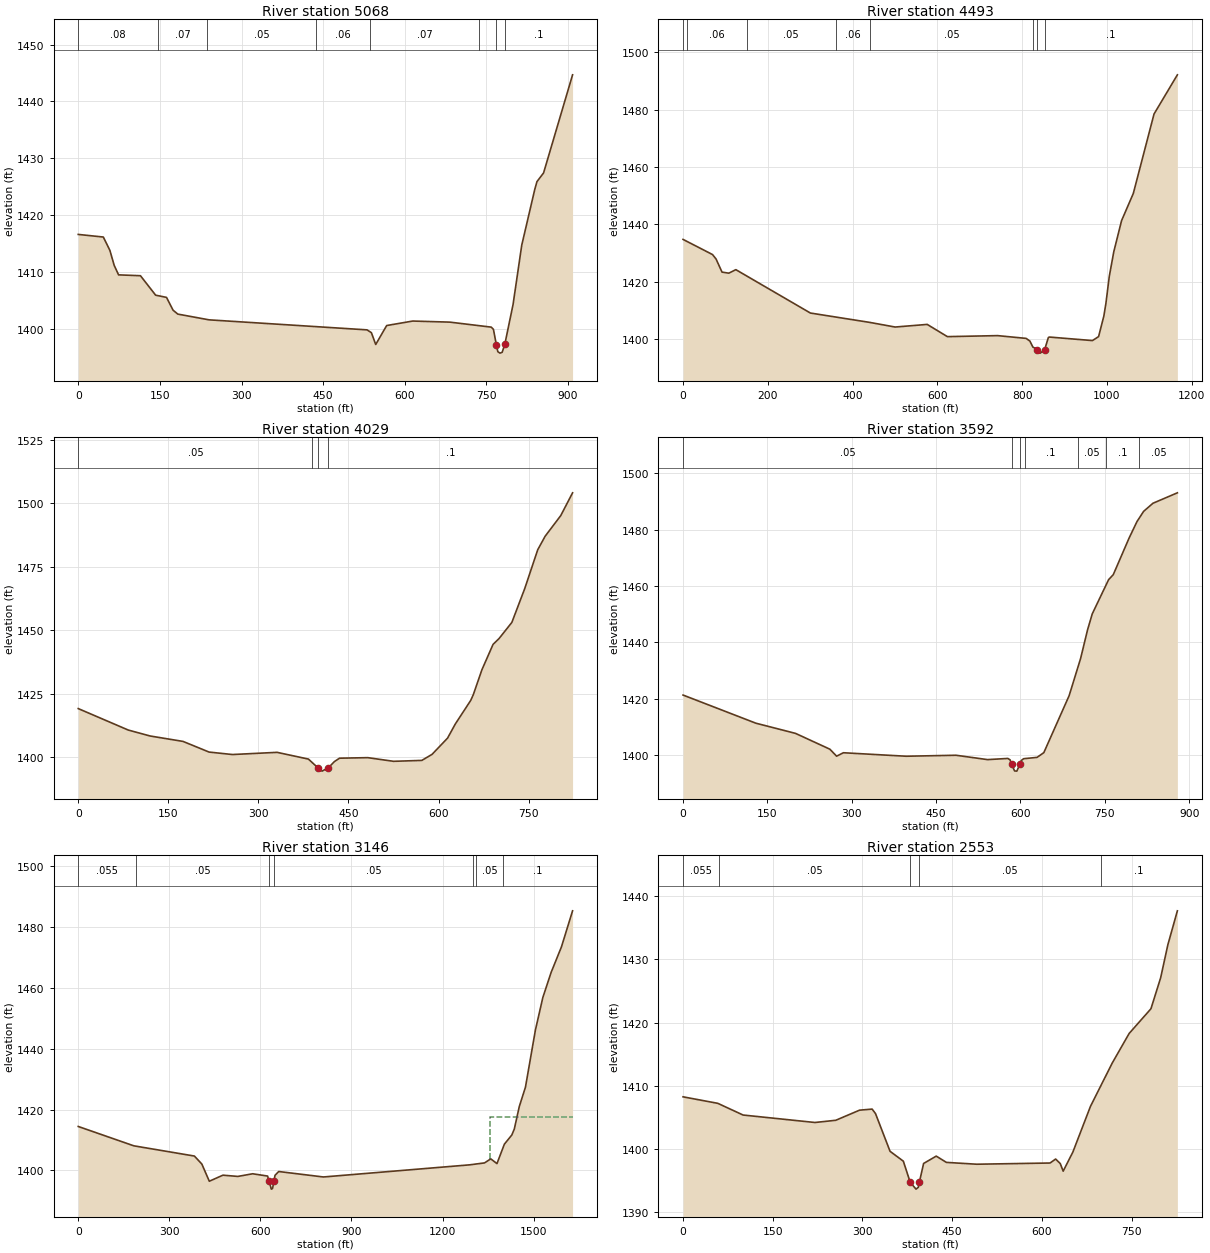
Type RM Length L Ch R = 1 ,5068    ,581.7,574.7,567.2
XS GIS Cut Line= 3
2192891.51353614740551.1925987072192896.90998412 740454.64233615
2192859.74919125739643.928375692
#Sta/Elev= 30
       0 1416.61    46.1 1416.15    58.1 1413.81    66.1 1411.16    74.1  1409.5
   114.3 1409.35   142.2 1405.93   162.2 1405.54   174.2 1403.29     183  1402.6
   240.5 1401.59   530.6 1399.83   538.6 1399.34   546.6 1397.26   566.7 1400.59
   614.7 1401.38   682.8 1401.19   758.9 1400.31   762.9 1399.92   768.21397.237
   770.9    1396   774.9 1395.74   778.9 1395.88  783.781397.287   798.9 1404.26
   814.9 1414.72   838.9 1424.55   842.9  1425.9     855 1427.42   908.3 1444.67
#Mann= 8 ,-1,0
       0     .08       0   146.7     .07       0   236.7     .05       0
   436.7     .06       0   536.7     .07       0   736.7      .1       0
   768.2    .045       0  783.78      .1       0
Bank Sta=768.2,783.78
XS Rating Curve= 0 ,0
Exp/Cntr=0.3,0.1

Type RM Length L Ch R = 1 ,4493    ,472.4,464.7,456.1
XS GIS Cut Line= 4
2193994.74419548740316.5775537322193582.56868498739927.836795908
2193343.42182379739564.7925552922193218.19617245739457.508377635
#Sta/Elev= 30
       0  1434.7    69.5 1429.41    77.8 1427.87    91.9 1423.28     108 1422.91
   124.5 1424.14   300.4 1408.99     440 1405.73   500.5  1404.1     576 1405.02
   623.6 1400.75   742.2  1401.1   809.3 1400.14   818.2 1399.21   825.4  1397.1
   835.9 1396.23   842.8 1394.99   853.11396.218   861.9 1400.47   864.8  1400.6
   965.8 1399.37   980.3 1400.76   992.7 1407.91   997.6 1412.36  1005.6 1421.82
  1016.1 1430.34  1034.5 1441.24  1062.2 1450.74  1111.1 1478.48  1166.2 1492.17
#Mann= 8 ,-1,0
       0     .08       0      10     .06       0     150     .05       0
     360     .06       0     440     .05       0  826.58      .1       0
   835.9    .045       0   853.1      .1       0
Bank Sta=835.9,853.1
XS Rating Curve= 0 ,0
Exp/Cntr=0.3,0.1

Type RM Length L Ch R = 1 ,4029    ,442.2,436.9,432.9
XS GIS Cut Line= 3
     2194092.459       739513.99     2193716.434      739352.724
     2193329.814      739204.614
#Sta/Elev= 30
       0 1419.23    83.2 1410.79   119.6 1408.45   174.5 1406.31   217.9 1402.12
   256.7 1401.15   331.1 1402.01   383.3 1399.36  398.95 1395.97     406 1394.62
   416.61395.953   426.6 1398.38   435.1 1399.71   482.2 1399.92   525.1 1398.48
   572.2 1398.84   589.3 1401.24     615  1407.6   627.9 1413.16   653.7 1422.49
   657.9 1424.71   672.2 1434.49   690.8  1444.5   700.7 1446.77   722.1 1453.14
   743.5 1466.43   765.2 1481.74   777.5 1487.04   803.5 1495.17   823.2 1504.13
#Mann= 4 ,-1,0
       0     .05       0     390      .1       0  398.95    .045       0
   416.6      .1       0
Bank Sta=398.95,416.6
XS Rating Curve= 0 ,0
Exp/Cntr=0.3,0.1

Type RM Length L Ch R = 1 ,3592    ,443.6,445.8,447.4
XS GIS Cut Line= 4
2194328.98793995739002.4204928372194109.78860997738941.862769335
 2193666.3648611738917.4849465592193466.34578533738973.069096402
#Sta/Elev= 30
       0 1421.25   129.5 1411.25     200 1407.63   261.1 1402.01   273.1 1399.53
   285.1 1400.75   396.7 1399.51   485.4 1399.86   541.5 1398.31   577.6 1398.73
   581.6 1398.22   584.31396.626   589.6 1394.29   593.6 1394.22  598.861396.611
   601.7 1398.02   605.7 1398.63   629.6 1399.11   641.6 1400.79   686.6 1421.03
     707 1434.24   719.4 1444.45   727.7 1450.08   756.8 1462.25   765.1 1464.03
   793.2 1477.01   807.3  1482.9   819.1 1486.52   835.7  1489.4   879.1  1493.1
#Mann= 7 ,-1,0
       0     .05       0   584.3    .045       0  598.86     .05       0
  607.41      .1       0   701.5     .05       0   751.5      .1       0
   811.5     .05       0
Bank Sta=584.3,598.86
XS Rating Curve= 0 ,0
Exp/Cntr=0.3,0.1

Type RM Length L Ch R = 1 ,3146    ,590.6,592.8,593.9
XS GIS Cut Line= 3
2194404.21298914738638.4530704262194029.60163303 738532.21135303
2192816.22503014738281.544745931
#Sta/Elev= 30
       0 1414.44     183 1408.09   382.6 1404.73   407.2  1402.1   431.7 1396.46
   476.6 1398.45   525.6 1398.04   574.6 1398.91   623.7 1398.16  628.921396.458
   635.9 1393.87     640 1394.05   644.71396.508   648.2 1398.41   660.4 1399.65
   807.5 1397.86  1289.4 1401.84  1338.4 1402.48  1358.9 1403.81  1379.3 1402.25
  1403.8 1408.64  1428.3 1411.65  1436.5 1413.61  1452.9    1421  1473.2 1427.35
  1505.9 1446.06  1530.4 1456.77  1557.6 1464.98  1591.7 1473.39  1628.4 1485.24
#Mann= 7 ,-1,0
       0    .055       0     190     .05       0  628.92    .045       0
   644.7     .05       0 1299.39      .1       0 1309.39     .05       0
 1399.39      .1       0
#XS Ineff= 2 , 0
                         1356.44         1417.66
Permanent Ineff=
       F       F
Bank Sta=628.92,644.7
XS Rating Curve= 0 ,0
Exp/Cntr=0.3,0.1

Type RM Length L Ch R = 1 ,2553    ,222.6,227.9,233.2
XS GIS Cut Line= 4
2194280.13454762738075.9299365062193994.50704762737932.929206354
2193654.65266053737815.7093387962193508.43012697737794.187238108
#Sta/Elev= 30
       0 1408.25    58.1 1407.22   100.4 1405.37   220.6 1404.19   255.4 1404.54
   295.2 1406.14   316.2 1406.31   321.9 1405.59   346.2 1399.63   368.4 1398.07
  379.861394.738   389.6 1393.65   393.4 1393.93   395.21394.755   402.3 1397.71
   423.4 1398.87   440.4 1397.88   491.1 1397.59   613.8 1397.78   623.1 1398.41
   630.8  1397.7   635.7 1396.49   651.9 1399.51   681.4 1406.75   717.8  1413.6
   746.1 1418.28   782.5 1422.18   798.7 1427.07   810.8 1432.31   826.7 1437.67
#Mann= 5 ,-1,0
       0    .055       0      60     .05       0  379.86    .045       0
   395.2     .05       0  698.93      .1       0
Bank Sta=379.86,395.2
XS Rating Curve= 0 ,0
Exp/Cntr=0.3,0.1

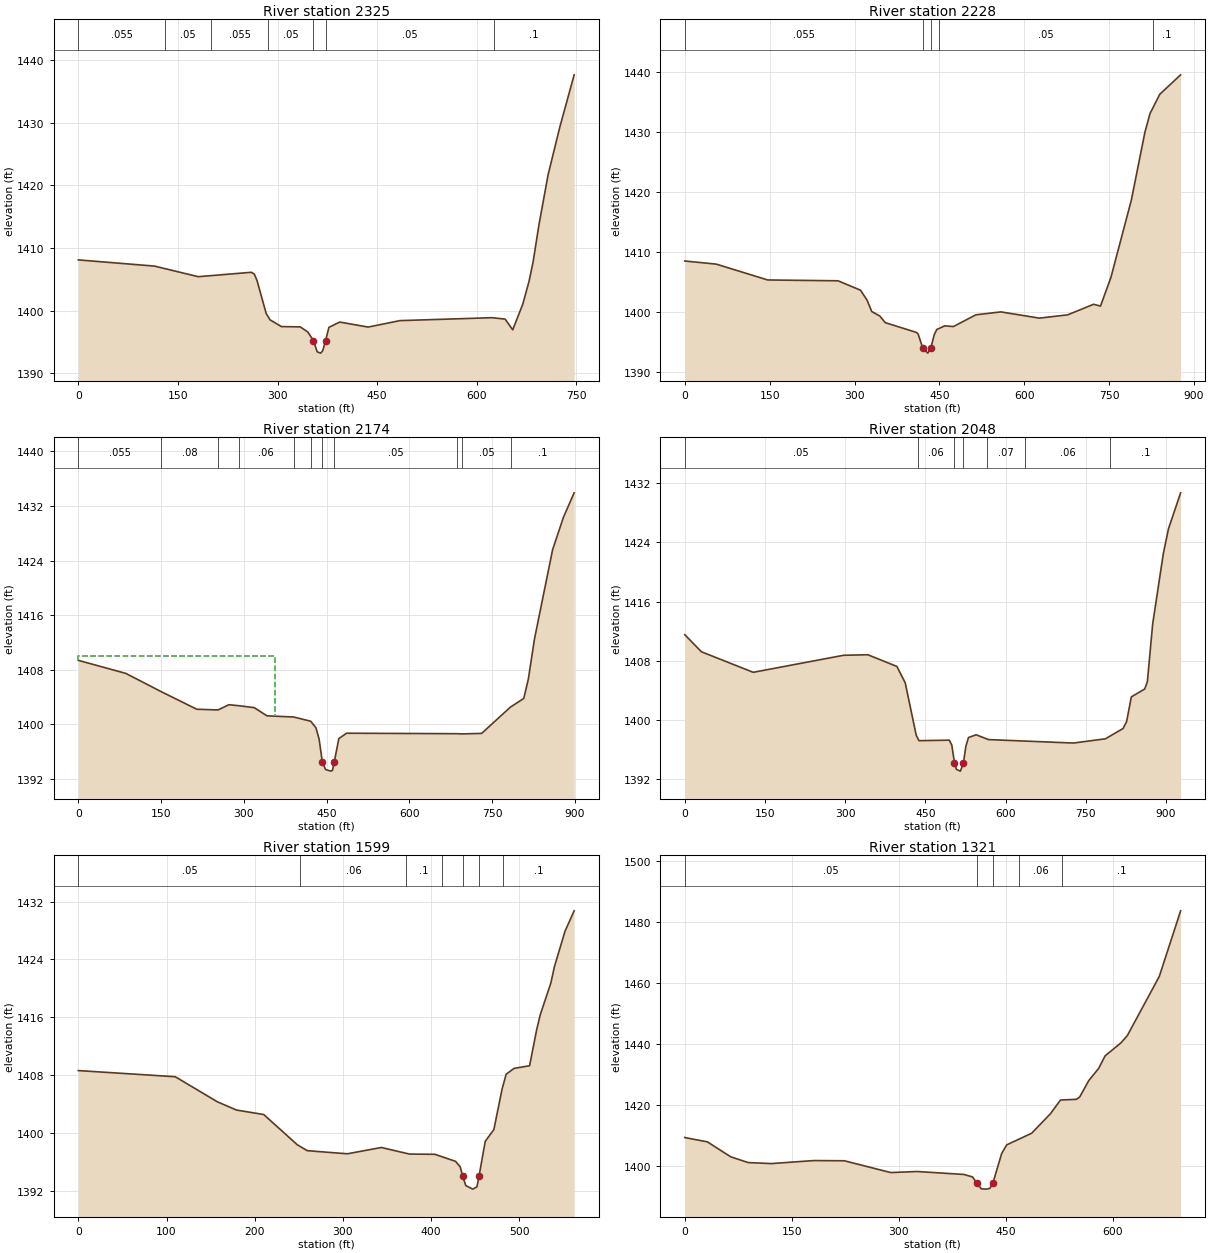
Type RM Length L Ch R = 1 ,2325    ,96,97,98.2
XS GIS Cut Line= 3
2194305.16424162738012.6741040522194153.01943331737807.889272552
2193791.24556273737475.313922735
#Sta/Elev= 30
       0 1408.11   114.7 1407.12   180.5 1405.43   260.5 1406.13     265 1405.83
     269 1404.83   282.8 1399.56   288.7 1398.53   305.8 1397.46   334.1 1397.41
   345.4 1396.61     354 1395.22   359.6 1393.43   364.9 1393.22     368 1393.62
  372.161395.163   377.3 1397.34   393.5 1398.18   436.4 1397.38   484.1 1398.41
   622.8 1398.88   642.6 1398.65     654 1396.94   669.2 1401.05   678.8 1404.78
   684.7  1407.8   693.6 1413.77   707.2 1421.67   724.7 1429.24   746.5 1437.67
#Mann= 7 ,-1,0
       0    .055       0     130     .05       0     200    .055       0
  285.12     .05       0     354    .045       0  372.16     .05       0
  625.12      .1       0
Bank Sta=354,372.16
XS Rating Curve= 0 ,0
Exp/Cntr=0.3,0.1

Type RM Length L Ch R = 1 ,2228    ,54.9,54.8,55.1
XS GIS Cut Line= 6
2194438.78557214737981.6572492892194031.76066427737548.656656416
2194009.93929561737519.9993206512193984.63515918737482.479394218
2193955.84079703 737416.165105642193866.53596288737323.804441405
#Sta/Elev= 30
       0 1408.52    55.6    1408   146.5 1405.36     271 1405.22   310.6 1403.65
     322 1402.02   330.4  1400.1   344.6 1399.36   354.2 1398.25   409.7 1396.61
   412.5 1396.33   420.71393.978   429.5 1393.17   434.61393.957   440.8 1396.22
   445.3  1397.1   459.3 1397.71   474.8  1397.6   514.4 1399.55   558.6 1400.04
   626.6    1399   676.7 1399.55   722.5 1401.31   734.7 1401.01   753.1 1405.78
   789.3  1418.7   813.2 1429.98   822.2 1433.08   839.4 1436.29   876.3 1439.54
#Mann= 5 ,-1,0
       0    .055       0   420.7    .045       0   434.6    .055       0
     450     .05       0  827.84      .1       0
Bank Sta=420.7,434.6
XS Rating Curve= 0 ,0
Exp/Cntr=0.3,0.1

Type RM Length L Ch R = 1 ,2174    ,127.9,126,124
XS GIS Cut Line= 6
2194495.00696598 737961.485503892194087.98205811737528.484911017
2194040.85655301737462.3076488192194023.02764204737424.890669927
2194009.44452158737361.0911030952193928.86525171737277.456003146
#Sta/Elev= 30
       0 1409.36    85.9 1407.45   150.1 1404.77   214.5 1402.19     253 1402.08
   272.8 1402.85   290.3 1402.71   318.8 1402.42   341.8 1401.22   390.2 1401.05
     421 1400.43   430.5 1399.48   436.3 1397.79   442.1 1394.48     448 1393.34
   457.8 1393.11   460.6 1393.25  463.761394.456     472 1397.88   486.1 1398.67
   685.7  1398.6   695.7 1398.57   730.7 1398.64   783.1 1402.51   807.1 1403.77
   815.4 1406.61   826.5 1412.49   859.4  1425.6   879.2 1430.39   898.4 1433.93
#Mann= 11 ,-1,0
       0    .055       0   150.1     .08       0     253    .055       0
   290.3     .06       0   390.2    .055       0     421     .05       0
   442.1    .045       0  463.76     .05       0   685.7     .06       0
   695.7     .05       0   783.1      .1       0
#XS Ineff= 2 , 0
          356.43    1410
Permanent Ineff=
       F       F
Bank Sta=442.1,463.76
XS Rating Curve= 0 ,0
Exp/Cntr=0.3,0.1

Type RM Length L Ch R = 1 ,2048    ,453.3,448.6,453.1
XS GIS Cut Line= 5
2194706.69228818737770.668311787  2194453.417324737615.328077424
2194364.64229587737616.5669798812194007.05529627737325.422811669
2193941.71523048737278.469726225
#Sta/Elev= 30
       0 1411.54    31.1 1409.23     128 1406.46   297.1 1408.76   342.4 1408.83
   396.8 1407.25   412.3 1405.05   432.9 1397.97   438.1 1397.23   494.8  1397.3
   499.5 1396.62  504.491394.238   508.1 1393.36   515.5 1393.12   521.11394.191
   525.8 1396.48   530.6 1397.65     545 1398.03   567.8 1397.38     727 1396.91
   786.7 1397.48   819.8 1398.87   826.5 1399.81   835.3 1403.14   860.4 1404.21
   865.3  1405.2   875.2 1412.97   895.1 1422.46   904.8 1425.84   927.5 1430.69
#Mann= 7 ,-1,0
       0     .05       0   435.9     .06       0  504.49    .045       0
   521.1     .06       0   565.9     .07       0   635.9     .06       0
   795.9      .1       0
Bank Sta=504.49,521.1
XS Rating Curve= 0 ,0
Exp/Cntr=0.3,0.1

Type RM Length L Ch R = 1 ,1599    ,282.6,278.2,271.2
XS GIS Cut Line= 4
2194453.67928074737451.1098619652194267.31846326737373.549290528
2194014.16937593 737213.041996862193953.84448704737208.733076225
#Sta/Elev= 30
       0 1408.66   109.9 1407.81   157.6 1404.35   179.3 1403.21   210.2 1402.59
   248.2 1398.42   259.5  1397.6     305 1397.17   343.5 1398.04   375.4 1397.13
   404.2  1397.1   427.6 1396.13   432.9 1395.37   435.81394.072   439.2 1392.79
   447.1 1392.29   451.9 1392.61  454.261394.084   461.3 1398.89   471.1 1400.52
   480.3 1406.06     485 1408.15   493.9 1408.96   511.6 1409.33   519.6  1414.3
   523.7 1416.38   535.7 1420.76   539.7 1422.99   551.7 1427.89   562.1 1430.72
#Mann= 7 ,-1,0
       0     .05       0  251.86     .06       0  371.86      .1       0
  411.86     .06       0   435.8    .045       0  454.26     .06       0
  481.86      .1       0
Bank Sta=435.8,454.26
XS Rating Curve= 0 ,0
Exp/Cntr(USF)=0,0
Exp/Cntr=0.3,0.1

Type RM Length L Ch R = 1 ,1321    ,470.6,461.6,454.6
XS GIS Cut Line= 3
2194583.18985732737087.7806586162194123.90813571736992.552364284
2193921.40145001736891.958785711
#Sta/Elev= 30
       0 1409.21    31.7 1407.79    64.4 1402.89    88.9    1401   121.5 1400.67
   180.7 1401.66   223.7 1401.59   288.6 1397.73   325.8 1398.07   391.2 1397.11
   403.4  1396.3409.55711394.294   415.7 1392.38   423.1 1392.29   427.9 1392.56
     432 1394.27   444.3 1403.98   451.4 1406.82   486.3 1410.61   512.6 1417.01
   526.8 1421.52   549.1 1421.76   553.6 1422.48   566.5 1427.93   580.4 1431.93
   589.3    1436   611.7 1440.32   620.6 1442.71   665.3 1462.07   695.2 1483.59
#Mann= 5 ,-1,0
       0     .05       0409.5571    .045       0     432     .05       0
  469.05     .06       0  529.05      .1       0
Bank Sta=409.5571,432
XS Rating Curve= 0 ,0
Exp/Cntr=0.3,0.1

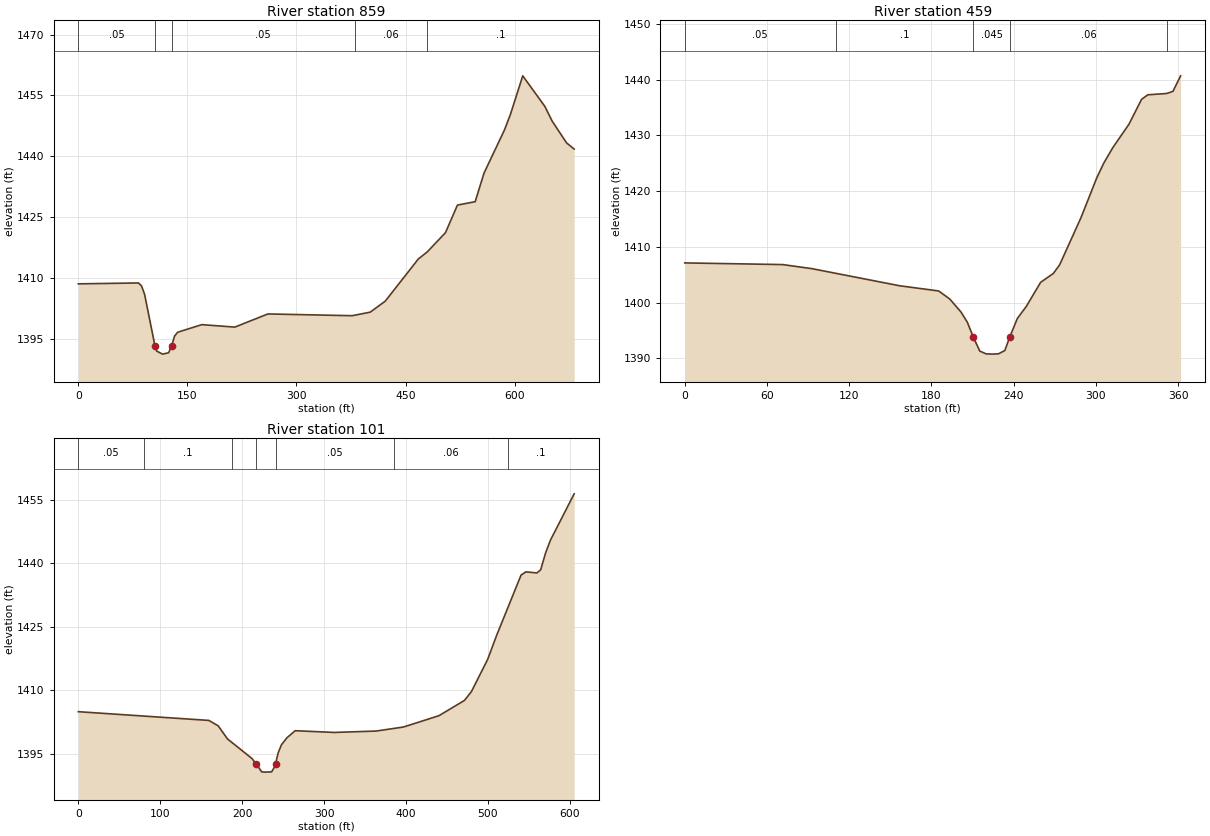
Type RM Length L Ch R = 1 ,859     ,413,399.7,387
XS GIS Cut Line= 4
 2194588.2070243736693.519936532 2194076.8656008736828.918943533
2193995.42825239736817.7412682612194043.47007837736765.821879047
#Sta/Elev= 30
       0 1408.63    82.8 1408.85    86.9 1408.13    91.1 1406.08  105.33 1393.43
   107.7 1392.09   115.9 1391.33   124.2 1391.67   128.3 1393.38   132.4 1395.78
   136.6 1396.72   169.9 1398.59   215.2 1397.98   260.7 1401.22   376.6 1400.79
   401.4 1401.66   422.1 1404.37   467.6 1414.75     480 1416.52   504.9 1421.22
   521.4 1428.02   545.8 1428.86   557.9 1435.88   585.9 1446.45   594.3 1450.36
   611.2 1459.84   641.7 1452.29   651.7 1448.68   671.5 1443.33   681.9 1441.81
#Mann= 5 ,-1,0
       0     .05       0  105.33    .045       0   128.3     .05       0
     380     .06       0     480      .1       0
Bank Sta=105.33,128.3
XS Rating Curve= 0 ,0
Exp/Cntr(USF)=0,0
Exp/Cntr=0.3,0.1

Type RM Length L Ch R = 1 ,459     ,341.7,358.2,367.4
XS GIS Cut Line= 4
2194334.33434743736484.2131199212194142.03051924736519.904333865
2194114.74210223736569.5578031292194019.32805676736623.625762231
#Sta/Elev= 30
       0 1407.14    71.4 1406.84      93  1406.1   156.8 1403.04   185.3 1402.11
   193.4 1400.66   201.6 1398.33   206.2 1396.51   210.7 1393.77   215.3 1391.33
   219.9 1390.83   224.4 1390.78     229 1390.84   233.6 1391.43  237.071393.772
   242.7 1397.16   249.3 1399.35   259.7 1403.65     269 1405.25   273.6  1406.8
   289.1 1415.21   300.8 1422.46   305.8 1425.03   312.5 1427.85   324.2 1432.01
   333.4 1436.48     338 1437.29   351.7 1437.52   356.3 1437.91   361.9 1440.69
#Mann= 5 ,-1,0
       0     .05       0     110      .1       0   210.7    .045       0
  237.07     .06       0  352.25      .1       0
Bank Sta=210.7,237.07
XS Rating Curve= 0 ,0
Exp/Cntr(USF)=0,0
Exp/Cntr=0.3,0.1

Type RM Length L Ch R = 1 ,101     ,,,
XS GIS Cut Line= 5
2194295.47538717 736299.618746612194151.71822532736234.101102051
2194116.09698168736199.1159520442194059.48464803736204.840794773
2193806.31938071736432.562316637
#Sta/Elev= 30
       0 1404.96   159.3  1402.9   170.7 1401.63   182.1 1398.53   211.9 1393.92
     217 1392.65   223.9 1390.75   227.9 1390.69     236 1390.76     240 1392.07
  240.761392.672     244 1395.26     248 1397.16   254.7 1398.81   264.8 1400.47
   312.3 1400.06   363.7 1400.39   396.9 1401.34   440.2 1404.01   471.3 1407.61
   479.8 1409.67   499.7  1417.3   510.5  1422.9   540.5 1437.22   546.4 1437.98
   559.8 1437.72   564.4 1438.45   570.5 1442.48   576.3 1445.44   605.3  1456.4
#Mann= 7 ,-1,0
       0     .05       0      80      .1       0  187.98     .05       0
     217    .045       0  240.76     .05       0  384.81     .06       0
  524.81      .1       0
Bank Sta=217,240.76
XS Rating Curve= 0 ,0
Exp/Cntr(USF)=0,0
Exp/Cntr=0.3,0.1
LCMann Table=0

Chan Stop Cuts=-1
Use User Specified Reach Order=0
Composite Channel Slope=5